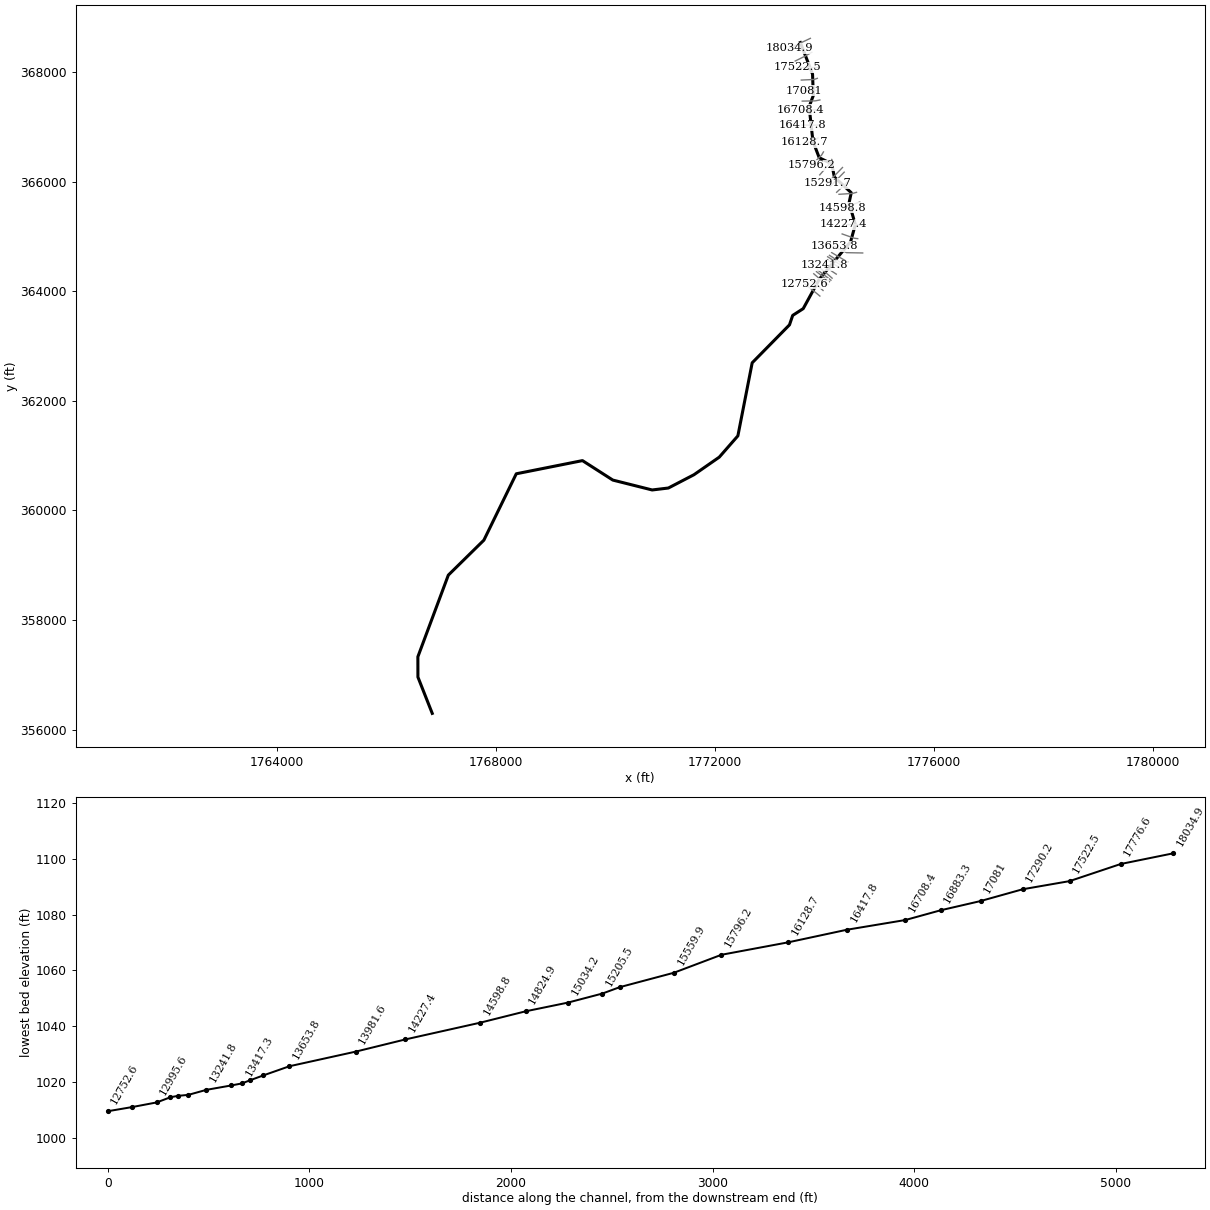
--- WHITESBR.prj (project) ---

Proj Title=WHITESBR
Current Plan=p01
Default Exp/Contr=0,0
English Units
Geom File=g01
Flow File=f01
Plan File=p01
BEGIN DESCRIPTION:
END DESCRIPTION:
DSS Export Rating Curves= 0
DSS Export Rating Curve Sorted= 0
DSS Export Volume Flow Curves= 0
DXF OffsetX= 0
DXF OffsetY= 0
DXF ScaleX= 0
DXF ScaleY= 0

--- WHITESBR.p01 (plan) ---

Plan Title=Floodplain
Program Version=4.00
Geom File=g01
Flow File=f01
K Sum by GR=0
Std Step Tol=0.01
Critical Tol=0.01
Num of Std Step Trials=20
Max Error Tol=0.3
Flow Tol Ratio=0.001
Split Flow NTrial=30
Split Flow Tol=0.02
Split Flow Ratio=0.02
Log Output Level=0
Friction Slope Method=1
Unsteady Friction Slope Method=2
Unsteady Bridges Friction Slope Method=1
Global Log Level=0
CheckData=False
Run HTab=0
Run UNet=0
Run PostProcess=0
UNET Theta=0
UNET Theta Warmup=0
UNET ZTol=0
UNET ZSATol=0
UNET MxIter=0
UNET MaxInSteps=0
UNET DtIC=0
UNET DtMin=0
UNET MaxCRTS=0
UNET WFStab=0
UNET SFStab=0
UNET WFX=0
UNET SFX=0
UNET DSS MLevel=0
UNET DZMax Abort=0
UNET Convert EG Bridges=0
UNET Use Existing IB Tables=0
UNET Froude Limit=0
UNET Froude Power=0
Write IC File=0
Echo Input=False
Echo Output=False
Write Detailed=0

--- WHITESBR.f01 (steady flow) ---

Flow Title=NFF Regression Equation
Program Version=4.10
Number of Profiles= 1
Profile Names=P100yr
River Rch & RM=WHITESBR,Main            ,18034.9
 800.295
River Rch & RM=WHITESBR,Main            ,17290.2
951.5778
River Rch & RM=WHITESBR,Main            ,15205.5
1012.485
River Rch & RM=WHITESBR,Main            ,13653.8
1305.735
River Rch & RM=WHITESBR,Main            ,9901.5
1431.713
River Rch & RM=WHITESBR,Main            ,9266.9
1617.581
River Rch & RM=WHITESBR,Main            ,7545.8
1754.255
River Rch & RM=WHITESBR,Main            ,6087.7
1862.445
River Rch & RM=WHITESBR,Main            ,648
2001.978
Boundary for River Rch & Prof#=WHITESBR,Main            , 1
Up Type= 0
Dn Type= 3
Dn Slope=0.013
DSS Import GetInterval= 0
DSS Import GetPeak= 0
DSS Import FillOption= 0

--- WHITESBR.g01 (geometry) ---

Geom Title=USGS 10m DEM
Program Version=4.10

River Reach=WHITESBR        ,Main
Reach XY= 30
     1773558.519      368540.651     1773781.044      367964.703
     1773795.627      367574.772     1773718.544      367367.898
     1773788.683      366736.925     1773903.266      366437.481
     1774131.594      366327.092     1774179.655      366085.397
     1774487.988      365799.356     1774448.259      365613.634
     1774562.988      365218.175     1774476.877      364905.258
     1773905.349      364221.231     1773610.761      363682.995
     1773418.544      363559.426     1773359.893      363386.988
     1772678.469       362694.28     1772417.155      361360.554
     1772076.877      360971.752     1771615.049      360651.285
     1771147.632      360408.387     1770851.183      360372.793
     1770132.433      360553.349     1769577.775      360908.689
     1768368.573      360668.238      1767776.53      359456.214
     1767127.224      358818.279       1766570.8      357327.741
     1766571.669      356957.082     1766833.295      356294.454

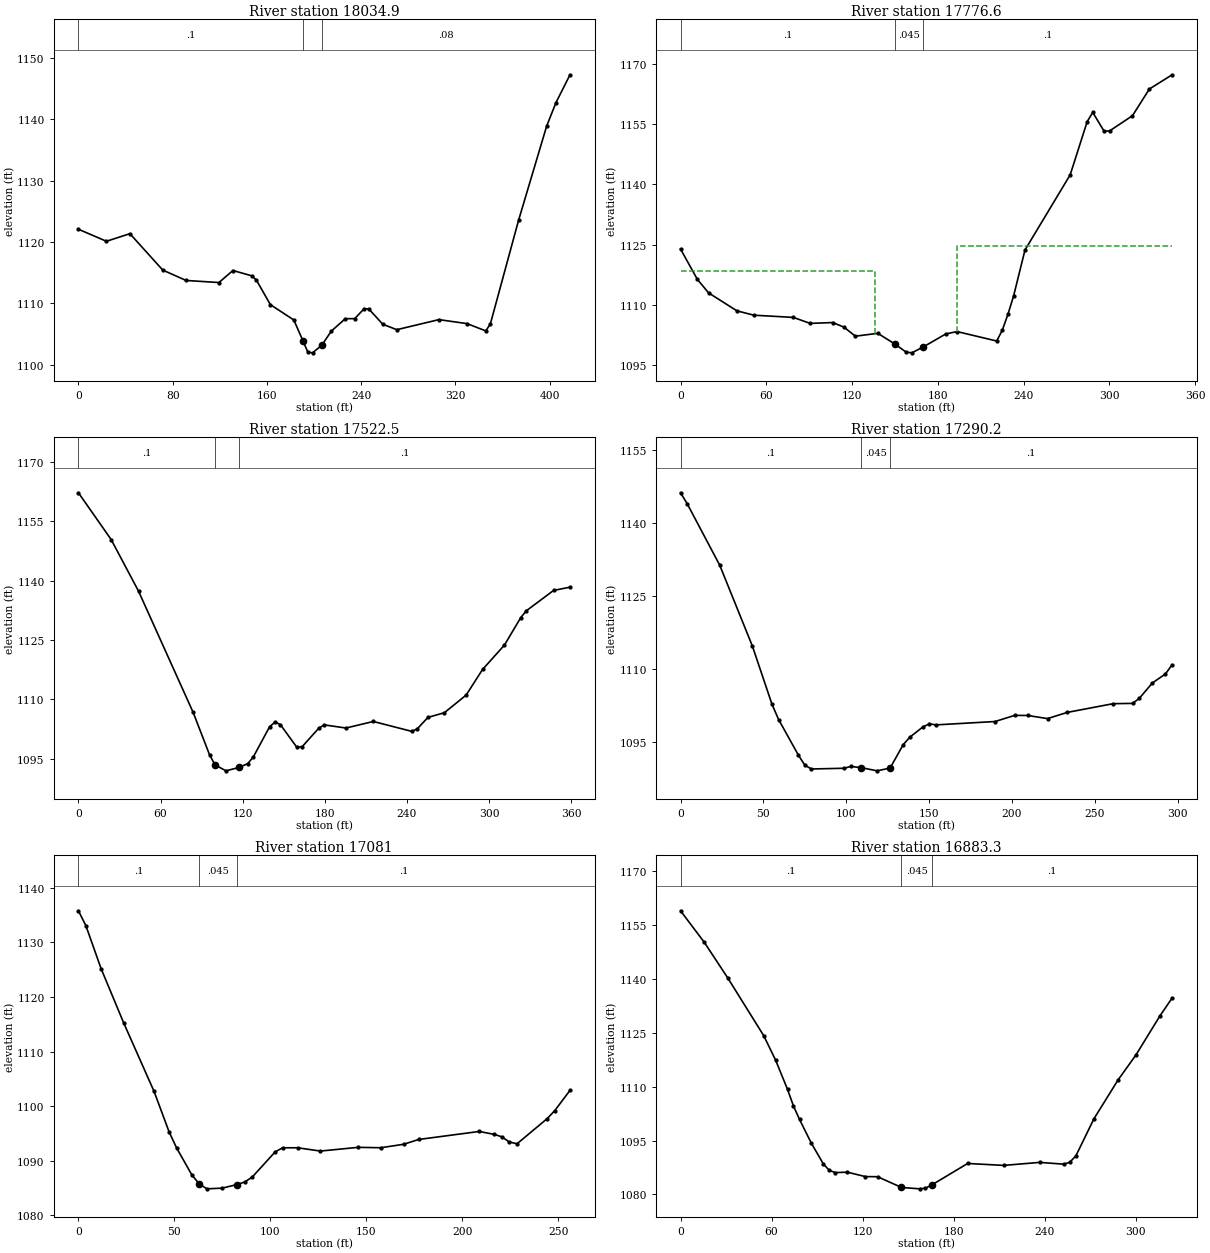
Type RM Length L Ch R = 1 ,18034.9 ,255.5,258.3,259
XS GIS Cut Line= 2
     1773741.584      368617.363      1773363.98      368439.411
#Sta/Elev= 30
       0 1122.06    23.8  1120.1    43.7 1121.34    71.6 1115.41    91.4 1113.72
   119.3 1113.38   131.2 1115.34   147.1 1114.48   151.1 1113.78     163 1109.78
   182.9 1107.28   190.8 1103.82   194.8 1102.04   198.8 1101.93   206.7 1103.18
   214.7 1105.46   226.6 1107.49   234.6  1107.5   242.5  1109.1   246.5 1109.09
   258.4 1106.59   270.3  1105.7   306.1 1107.34     330 1106.69   345.9  1105.5
   349.8 1106.65   373.7  1123.5   397.6 1138.87   405.5 1142.69   417.4 1147.22
#Mann= 3 , 0 , 0
       0      .1       0   190.8    .045       0   206.7     .08       0
Bank Sta=190.8,206.7
XS Rating Curve= 0 ,0
Exp/Cntr=0.3,0.1

Type RM Length L Ch R = 1 ,17776.6 ,273.6,254,236.2
XS GIS Cut Line= 3
     1773767.626      368363.457     1773645.013      368291.842
     1773463.806      368202.866
#Sta/Elev= 30
       0 1123.96    11.8 1116.39    19.7 1113.03    39.4 1108.59    51.3  1107.5
    78.9 1106.95    90.7 1105.46   106.5 1105.67   114.4 1104.52   122.3 1102.28
     138 1102.99   149.9 1100.35   157.8 1098.32   161.8 1098.14   169.7 1099.58
   185.5 1102.82   193.4 1103.43   221.2 1101.08   225.1 1103.77   229.1 1107.76
     233 1112.26     241 1123.72   272.6 1142.39   284.5 1155.63   288.4 1157.91
   296.4  1153.2   300.3 1153.34   316.2  1157.1     328 1163.73   343.9 1167.27
#Mann= 3 , 0 , 0
       0      .1       0   149.9    .045       0   169.7      .1       0
#XS Ineff= 2 , 0
          136.09 1118.57  193.45          1124.8
Permanent Ineff=
       F       F
Bank Sta=149.9,169.7
XS Rating Curve= 0 ,0
Exp/Cntr=0.3,0.1

Type RM Length L Ch R = 1 ,17522.5 ,229.3,232.3,234.3
XS GIS Cut Line= 2
     1773871.792      368088.934     1773512.634      368088.934
#Sta/Elev= 30
       0 1162.13    23.9 1150.34    43.9 1137.33    83.8 1106.76    95.8 1096.06
    99.8 1093.51   107.8    1092   117.6 1092.88   123.7 1093.82   127.7 1095.44
   139.7 1103.13   143.7  1104.3   147.6 1103.65   159.6 1097.94   163.6 1098.13
   175.6 1102.75   179.6 1103.59   195.5  1102.8   215.5 1104.45   243.4 1101.97
   247.4 1102.52   255.4 1105.48   267.4 1106.66   283.3  1111.1   295.3 1117.56
   311.3 1123.72   323.2 1130.64   327.2 1132.34   347.2  1137.5   359.2 1138.33
#Mann= 3 , 0 , 0
       0      .1       0    99.8    .045       0   117.6      .1       0
Bank Sta=99.8,117.6
XS Rating Curve= 0 ,0
Exp/Cntr=0.3,0.1

Type RM Length L Ch R = 1 ,17290.2 ,210.1,209.2,207.6
XS GIS Cut Line= 3
     1773868.537      367887.111     1773808.858      367866.495
     1773575.568      367855.644
#Sta/Elev= 30
       0 1146.15       4 1143.92    23.7 1131.26    43.4 1114.67    55.2 1102.75
    59.2 1099.62    71.1 1092.34      75 1090.26      79 1089.47    98.8 1089.62
   102.7 1089.99   108.9 1089.76   118.6 1089.09   126.5 1089.66   134.4 1094.46
   138.4    1096   146.3  1098.1   150.2 1098.73   154.2 1098.52   189.8 1099.21
   201.7 1100.47   209.6 1100.45   221.5 1099.81   233.4 1101.08   261.1 1102.87
   272.9 1102.93   276.9 1103.96   284.8 1107.12   292.7 1108.98   296.7 1110.84
#Mann= 3 , 0 , 0
       0      .1       0   108.9    .045       0   126.5      .1       0
Bank Sta=108.9,126.5
XS Rating Curve= 0 ,0
Exp/Cntr=0.3,0.1

Type RM Length L Ch R = 1 ,17081   ,194.4,197.7,200.4
XS GIS Cut Line= 2
     1773873.962      367667.927     1773617.886      367661.417
#Sta/Elev= 30
       0 1135.79     3.9 1133.05    11.8  1125.2    23.6 1115.24    39.4 1102.72
    47.3 1095.25    51.2 1092.33    59.1 1087.42      63 1085.74      67 1084.86
    74.9 1084.99    82.6 1085.64    86.7 1086.12    90.6 1087.02   102.5 1091.62
   106.4 1092.38   114.3 1092.38   126.1 1091.78   145.8 1092.46   157.6 1092.39
   169.5 1093.02   177.3  1093.9   208.9 1095.37   216.8 1094.83   220.7 1094.38
   224.6 1093.44   228.6 1093.11   244.3 1097.72   248.3  1099.2   256.2  1102.9
#Mann= 3 , 0 , 0
       0      .1       0      63    .045       0    82.6      .1       0
Bank Sta=63,82.6
XS Rating Curve= 0 ,0
Exp/Cntr=0.3,0.1

Type RM Length L Ch R = 1 ,16883.3 ,179.1,174.9,171
XS GIS Cut Line= 3
     1773915.195      367492.146      1773830.56       367475.87
     1773592.929      367471.529
#Sta/Elev= 30
       0 1159.03    15.7 1150.22    31.3  1140.2    54.8 1124.24    62.7 1117.38
    70.5 1109.27    74.4 1104.67    78.4  1100.9    86.2 1094.28    94.1  1088.5
    98.1 1086.68     102 1086.09     110  1086.2   121.8 1084.97   129.8 1084.94
   145.6 1081.95   157.5 1081.56   161.4 1081.74   165.4  1082.6   189.2 1088.63
   212.9 1088.09   236.7 1088.93   252.6 1088.43   256.5 1088.97   260.5 1090.74
   272.4 1101.08   288.2 1111.84   300.1 1118.87   315.9 1129.75   323.9 1134.71
#Mann= 3 , 0 , 0
       0      .1       0   145.6    .045       0   165.4      .1       0
Bank Sta=145.6,165.4
XS Rating Curve= 0 ,0
Exp/Cntr=0.3,0.1

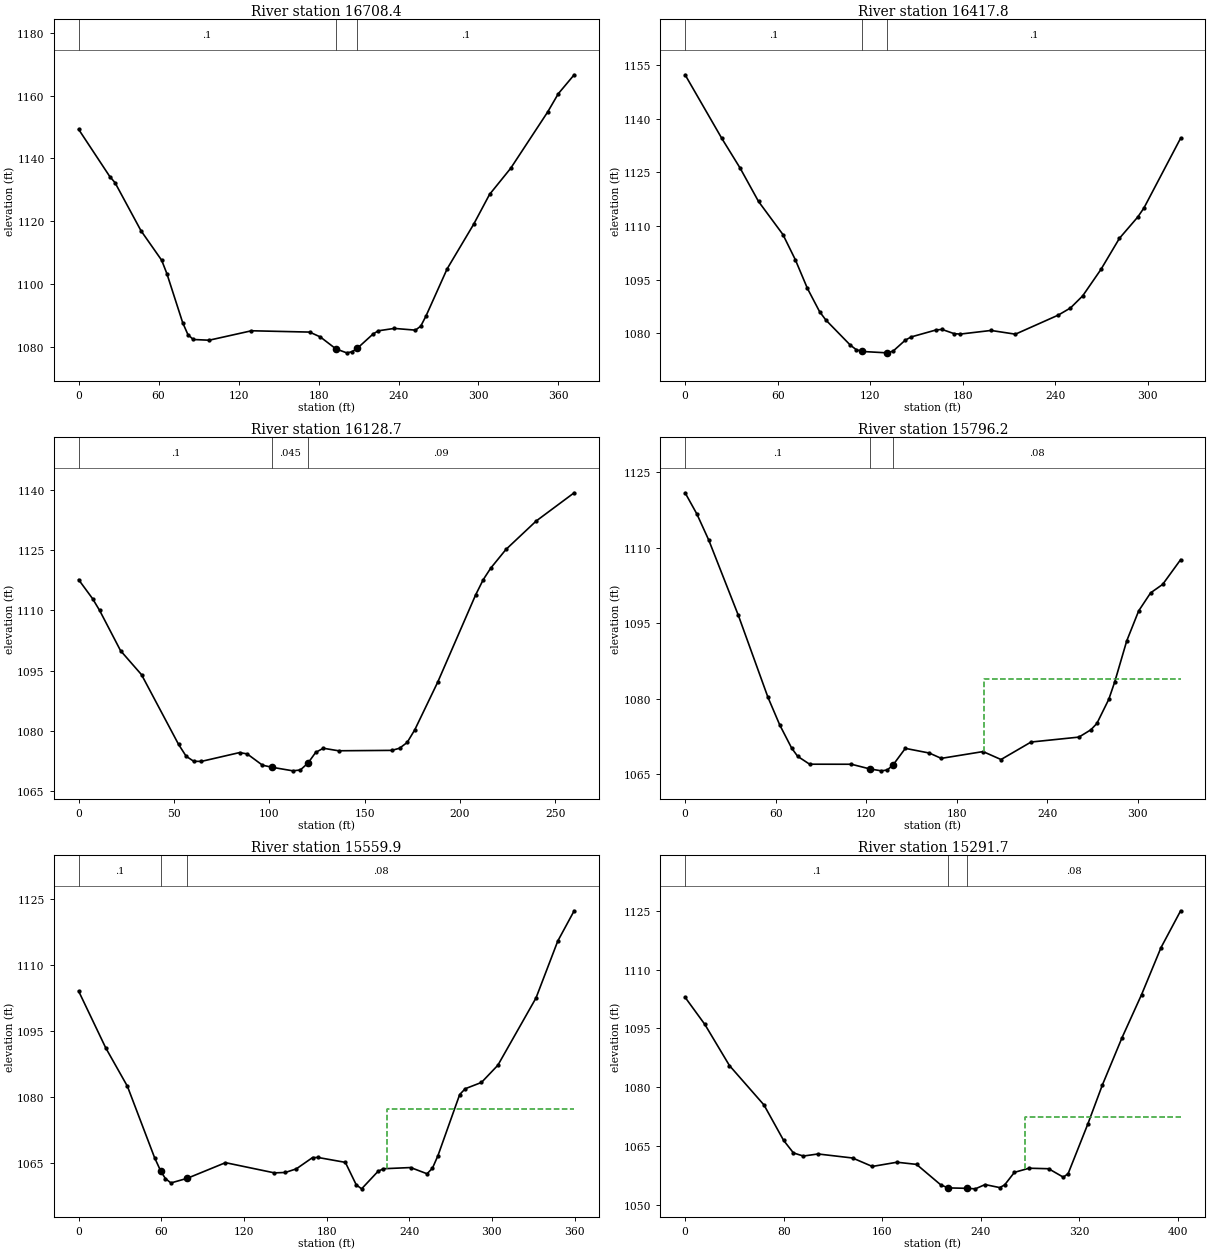
Type RM Length L Ch R = 1 ,16708.4 ,290.4,290.6,290.6
XS GIS Cut Line= 3
     1773924.961      367320.705     1773855.516      367310.939
     1773553.867      367310.939
#Sta/Elev= 30
       0 1149.25    23.4  1134.2    27.3 1132.27    46.8 1116.95    62.3 1107.56
    66.2 1103.31    78.1 1087.64      82 1083.88      86 1082.32    97.9 1082.09
   129.7  1085.1   173.3 1084.68   181.3 1083.14     193 1079.34   201.1 1078.07
   205.1 1078.41     209 1079.48     221  1084.1   224.9 1085.09   236.8 1085.85
   252.7  1085.3   256.7 1086.58   260.6 1089.78   276.5 1104.83   296.4 1119.03
   308.3 1128.52   324.2 1136.87   351.9 1154.77   359.9 1160.61   371.8 1166.63
#Mann= 3 , 0 , 0
       0      .1       0     193    .045       0     209      .1       0
Bank Sta=193,209
XS Rating Curve= 0 ,0
Exp/Cntr=0.3,0.1

Type RM Length L Ch R = 1 ,16417.8 ,272.8,289.1,305.3
XS GIS Cut Line= 2
     1773910.204       367032.51     1773589.023      367033.595
#Sta/Elev= 30
       0 1152.22    23.8 1134.45    35.7 1126.14    47.6 1116.84    63.4 1107.62
    71.4 1100.63    79.3 1092.56    87.2 1086.06    91.2 1083.76   107.1 1076.73
     111 1075.44   114.9 1074.96   130.8 1074.58   134.8 1075.05   142.8 1078.15
   146.7 1079.04   162.6 1080.96   166.5 1081.12   174.5 1079.92   178.4 1079.82
   198.3 1080.83   214.1 1079.79   241.9 1085.12   249.8 1087.11   257.7 1090.48
   269.6 1097.91   281.5 1106.54   293.4  1112.5   297.4 1115.02   321.2 1134.52
#Mann= 3 , 0 , 0
       0      .1       0   114.9    .045       0   130.8      .1       0
Bank Sta=114.9,130.8
XS Rating Curve= 0 ,0
Exp/Cntr=0.3,0.1

Type RM Length L Ch R = 1 ,16128.7 ,318.2,332.5,346.7
XS GIS Cut Line= 4
     1773880.473      366799.871     1773847.921         366776.
     1773724.223      366719.576     1773640.673      366717.406
#Sta/Elev= 30
       0 1117.63     7.3 1112.92      11 1109.99      22 1099.97      33    1094
    52.4 1076.69    56.4 1073.72    60.4 1072.47    64.4 1072.45    84.4 1074.64
    88.4 1074.31    96.4 1071.51   101.6 1070.97   112.4  1070.1   116.3 1070.32
   120.3 1072.03   124.3 1074.67   128.3 1075.72   136.3 1075.09   164.3 1075.19
   168.3 1075.72   172.3 1077.15   176.3  1080.3   188.3 1092.12   208.2 1113.83
   212.2 1117.63   216.1 1120.48   224.1 1125.14     240 1132.23   259.9 1139.24
#Mann= 3 , 0 , 0
       0      .1       0   101.6    .045       0   120.3     .09       0
Bank Sta=101.6,120.3
XS Rating Curve= 0 ,0
Exp/Cntr=0.3,0.1

Type RM Length L Ch R = 1 ,15796.2 ,224.8,236.3,238.1
XS GIS Cut Line= 3
     1773980.299      366543.795     1773946.662      366486.286
     1773761.115      366301.825
#Sta/Elev= 30
       0 1120.93     7.8 1116.71    15.7  1111.5    35.3 1096.53    54.9 1080.24
    62.7 1074.75    70.6 1070.14    74.6  1068.5    82.5 1066.94   110.2 1066.93
   122.4    1066     130 1065.62     134 1065.79     138 1066.88   145.9 1070.09
   161.8 1069.16   169.7  1068.1   197.4 1069.45   209.3 1067.87   229.2 1071.35
   260.9 1072.33   268.8 1073.78   272.8 1075.04   280.7 1079.85   284.6 1083.28
   292.6 1091.48   300.5 1097.44   308.4 1101.02   316.4 1102.71   328.3 1107.63
#Mann= 3 , 0 , 0
       0      .1       0   122.4    .045       0     138     .08       0
#XS Ineff= 2 , 0
                           198.1         1083.84
Permanent Ineff=
       F       F
Bank Sta=122.4,138
XS Rating Curve= 0 ,0
Exp/Cntr=0.3,0.1

Type RM Length L Ch R = 1 ,15559.9 ,276.3,268.1,266.3
XS GIS Cut Line= 3
     1774133.294      366405.991     1774114.848      366358.248
     1773913.025      366124.958
#Sta/Elev= 30
       0 1104.12    19.7  1091.2    35.4 1082.49    55.1 1066.28    59.7 1063.13
      63  1061.5      67 1060.51    78.9 1061.57   106.6 1065.12   142.1  1062.8
     150 1062.89     158 1063.71   169.8 1066.28   173.8  1066.3   193.6 1065.19
   201.5 1060.09   205.4 1059.17   217.3 1063.14   221.2 1063.74     241 1064.01
   252.9  1062.6   256.8 1063.85   260.8  1066.7   276.6 1080.61   280.6 1081.93
   292.4 1083.36   304.3 1087.27     332 1102.57   347.8 1115.51   359.7 1122.39
#Mann= 3 , 0 , 0
       0      .1       0    59.7    .045       0    78.9     .08       0
#XS Ineff= 2 , 0
                          223.56         1077.24
Permanent Ineff=
       F       F
Bank Sta=59.7,78.9
XS Rating Curve= 0 ,0
Exp/Cntr=0.3,0.1

Type RM Length L Ch R = 1 ,15291.7 ,87.5,86.2,84.1
XS GIS Cut Line= 3
     1774328.607      366259.507     1774195.143      366121.703
     1774048.659      365970.878
#Sta/Elev= 30
       0 1102.97      16 1096.05      36 1085.52      64 1075.46    79.9 1066.42
    87.9  1063.2    95.9  1062.4   107.9 1062.93   135.9  1061.9   151.9 1059.74
   171.9 1060.82   187.8 1060.27   207.7 1054.97   213.7 1054.26   228.7 1054.15
   235.5 1054.02   243.4 1055.11   255.3 1054.34   259.3 1055.03   267.2 1058.23
   279.1 1059.29     295 1059.16   306.9    1057   310.8  1057.9   326.7 1070.51
   338.6 1080.57   354.5 1092.62   370.4 1103.66   386.2 1115.69   402.1 1125.08
#Mann= 3 , 0 , 0
       0      .1       0   213.7    .045       0   228.7     .08       0
#XS Ineff= 2 , 0
                          275.91         1072.35
Permanent Ineff=
       F       F
Bank Sta=213.7,228.7
XS Rating Curve= 0 ,0
Exp/Cntr=0.3,0.1

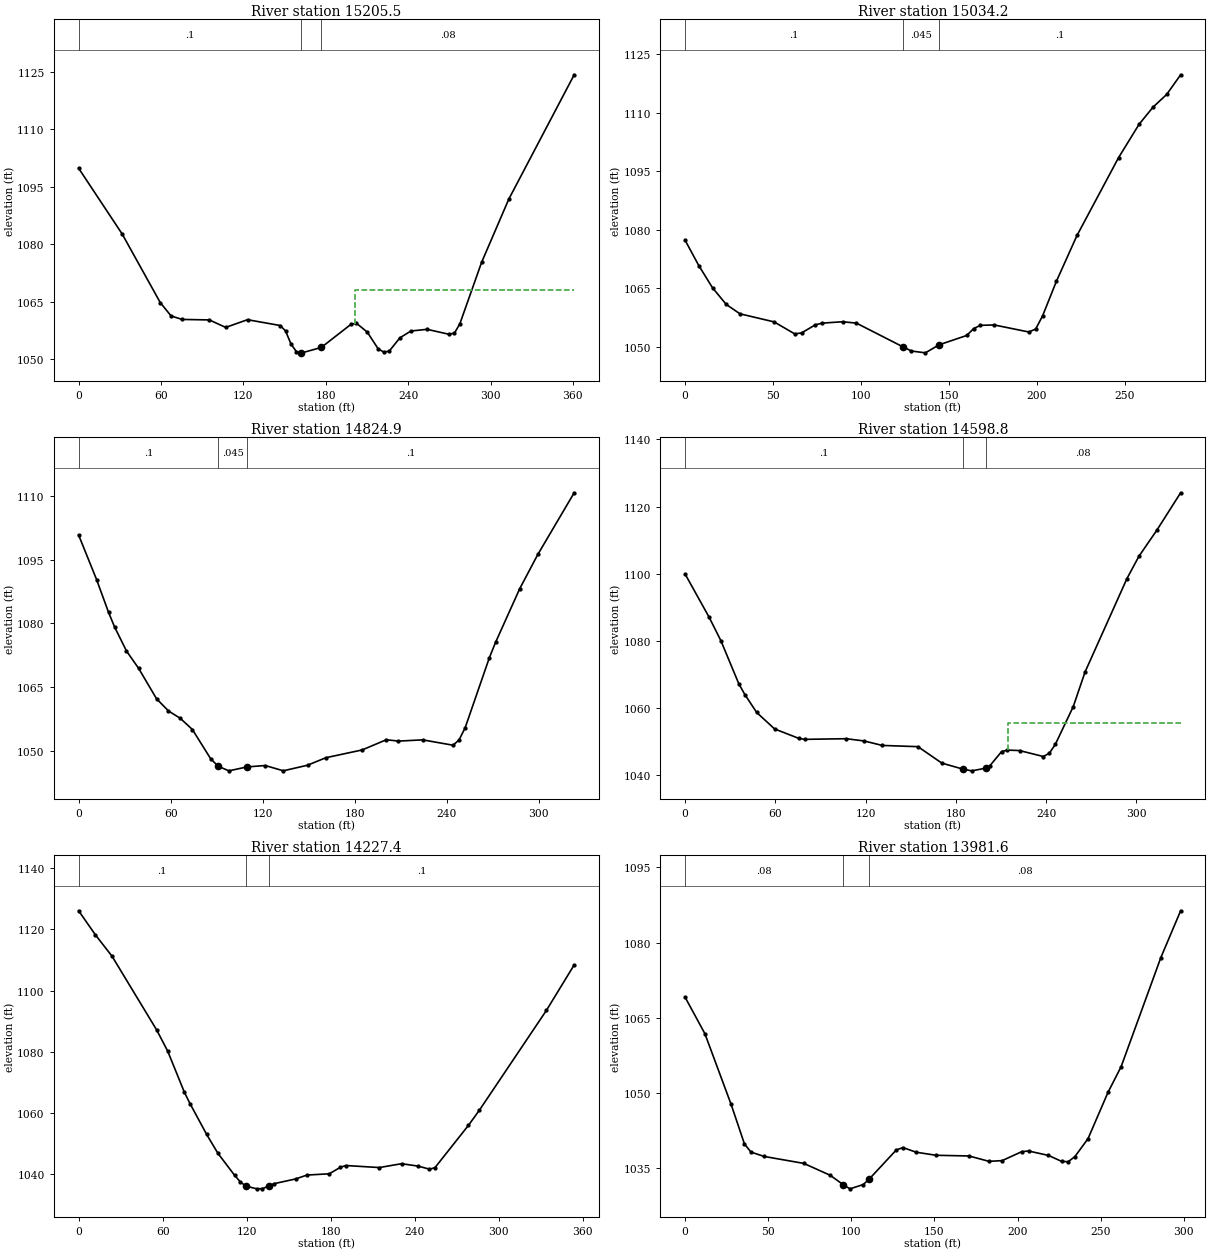
Type RM Length L Ch R = 1 ,15205.5 ,172.2,171.3,170.2
XS GIS Cut Line= 2
     1774359.509      366174.546     1774106.905      365916.733
#Sta/Elev= 30
       0 1099.85    31.7 1082.72    59.5  1064.8    67.4 1061.33    75.4 1060.44
    95.2 1060.31   107.1 1058.36     123 1060.37   146.8 1058.85   150.7 1057.45
   154.7    1054   158.6 1052.05   161.7  1051.8   162.6 1051.73   176.7 1053.13
   198.3 1059.15   202.3 1059.46   210.2 1057.14   218.2 1052.75   222.1 1051.96
   226.1 1052.13     234 1055.65     242 1057.42   253.8 1057.86   269.7 1056.57
   273.7 1056.88   277.6 1059.26   293.5 1075.34   313.3 1091.81   360.9 1124.22
#Mann= 3 , 0 , 0
       0      .1       0   161.7    .045       0   176.7     .08       0
#XS Ineff= 2 , 0
                          201.24         1068.06
Permanent Ineff=
       F       F
Bank Sta=161.7,176.7
XS Rating Curve= 0 ,0
Exp/Cntr=0.3,0.1

Type RM Length L Ch R = 1 ,15034.2 ,233.4,209.3,182.5
XS GIS Cut Line= 3
     1774424.093      366002.345     1774352.478      365930.731
     1774221.185      365807.033
#Sta/Elev= 30
       0 1077.33     7.8 1070.83    15.6 1065.14    23.4 1060.88    31.2 1058.48
    50.6 1056.41    62.3 1053.34    66.2 1053.58      74 1055.65    77.9 1056.09
    89.6 1056.45    97.4 1056.09   123.9    1050   128.7 1048.94   136.6 1048.48
   144.4 1050.54   160.1 1052.93     164 1054.69   167.9 1055.53   175.8 1055.62
   195.4 1053.82   199.3 1054.58   203.2 1057.93   211.1 1066.84   222.8 1078.57
   246.4 1098.49   258.1 1107.06     266 1111.43   273.8 1114.71   281.7 1119.73
#Mann= 3 , 0 , 0
       0      .1       0   123.9    .045       0   144.4      .1       0
Bank Sta=123.9,144.4
XS Rating Curve= 0 ,0
Exp/Cntr=0.3,0.1

Type RM Length L Ch R = 1 ,14824.9 ,218.6,226.1,236.2
XS GIS Cut Line= 3
     1774584.683      365805.948     1774513.068      365786.417
     1774264.587      365770.141
#Sta/Elev= 30
       0 1100.78    11.7 1090.33    19.5 1082.63    23.4 1079.22    31.2 1073.54
    39.1 1069.47    50.8 1062.32    58.6 1059.45    66.4 1057.68    74.2 1055.08
    86.1 1048.22      91 1046.45      98 1045.37   109.8 1046.29   121.7 1046.62
   133.5 1045.38   149.3 1046.69   161.2 1048.45   184.9 1050.28   200.7 1052.68
   208.6 1052.36   224.4 1052.65   244.2 1051.39   248.1 1052.62   252.1  1055.5
   267.9 1071.97   271.9 1075.54   287.7 1088.19   299.5 1096.23   323.2 1110.72
#Mann= 3 , 0 , 0
       0      .1       0      91    .045       0   109.8      .1       0
Bank Sta=91,109.8
XS Rating Curve= 0 ,0
Exp/Cntr=0.3,0.1

Type RM Length L Ch R = 1 ,14598.8 ,384.9,371.3,355.5
XS GIS Cut Line= 2
     1774644.362      365629.082     1774332.947       365521.66
#Sta/Elev= 30
       0  1099.9    15.9  1087.1    23.8 1080.04    35.7 1067.21    39.7 1064.02
    47.6 1058.66    59.5 1053.76    75.4 1050.98    79.4 1050.66   107.2 1050.85
   119.1 1050.17     131 1048.85   154.8 1048.48   170.7 1043.57     185 1041.76
   190.5 1041.28     200 1042.08   202.4 1042.69   210.4 1047.02   214.3 1047.46
   222.3 1047.32   238.1 1045.55   242.1  1046.5   246.1 1049.17     258 1060.39
   265.9 1070.77   293.7 1098.54   301.6 1105.14   313.6 1112.98   329.4 1124.11
#Mann= 3 , 0 , 0
       0      .1       0     185    .045       0     200     .08       0
#XS Ineff= 2 , 0
                          214.53         1055.56
Permanent Ineff=
       F       F
Bank Sta=185,200
XS Rating Curve= 0 ,0
Exp/Cntr=0.3,0.1

Type RM Length L Ch R = 1 ,14227.4 ,257.7,245.8,233.1
XS GIS Cut Line= 2
      1774691.02       365211.33     1774337.287       365220.01
#Sta/Elev= 30
       0 1126.06    11.9 1118.25    23.8 1111.26    55.7 1087.16    63.6 1080.23
    75.5 1066.81    79.5 1063.12    91.4 1053.05    99.4 1046.91   111.3 1039.73
   115.3 1037.63   119.3 1036.19   127.2 1035.28   131.2 1035.35   135.9  1036.2
   139.2 1036.93     155 1038.52     163 1039.78   178.9 1040.19   186.9 1042.31
   190.8 1042.89   214.7 1042.23   230.6 1043.49   242.5 1042.69   250.5  1041.7
   254.4 1042.19   278.3    1056   286.2    1061     334 1093.55   353.8 1108.38
#Mann= 3 , 0 , 0
       0      .1       0   119.3    .045       0   135.9      .1       0
Bank Sta=119.3,135.9
XS Rating Curve= 0 ,0
Exp/Cntr=0.3,0.1

Type RM Length L Ch R = 1 ,13981.6 ,332,327.8,322.1
XS GIS Cut Line= 3
     1774606.384      364960.679      1774543.45      364968.274
     1774322.096      365046.399
#Sta/Elev= 30
       0 1069.11    11.9 1061.85    27.7 1047.74    35.7 1039.87    39.6 1038.25
    47.5 1037.38    71.4 1035.99    87.3 1033.62    95.2 1031.73    99.2 1030.92
   107.2 1031.78   110.9 1032.92     127 1038.65     131 1039.15     139 1038.22
   150.9 1037.61   170.8 1037.47   182.8  1036.4   190.7 1036.54   202.6 1038.34
   206.6 1038.46   218.6 1037.58   226.5 1036.39   230.5 1036.33   234.5 1037.35
   242.4 1040.93   254.4 1050.15   262.3 1055.27   286.2 1077.02   298.1 1086.34
#Mann= 3 , 0 , 0
       0     .08       0    95.2    .045       0   110.9     .08       0
Bank Sta=95.2,110.9
XS Rating Curve= 0 ,0
Exp/Cntr=0.3,0.1

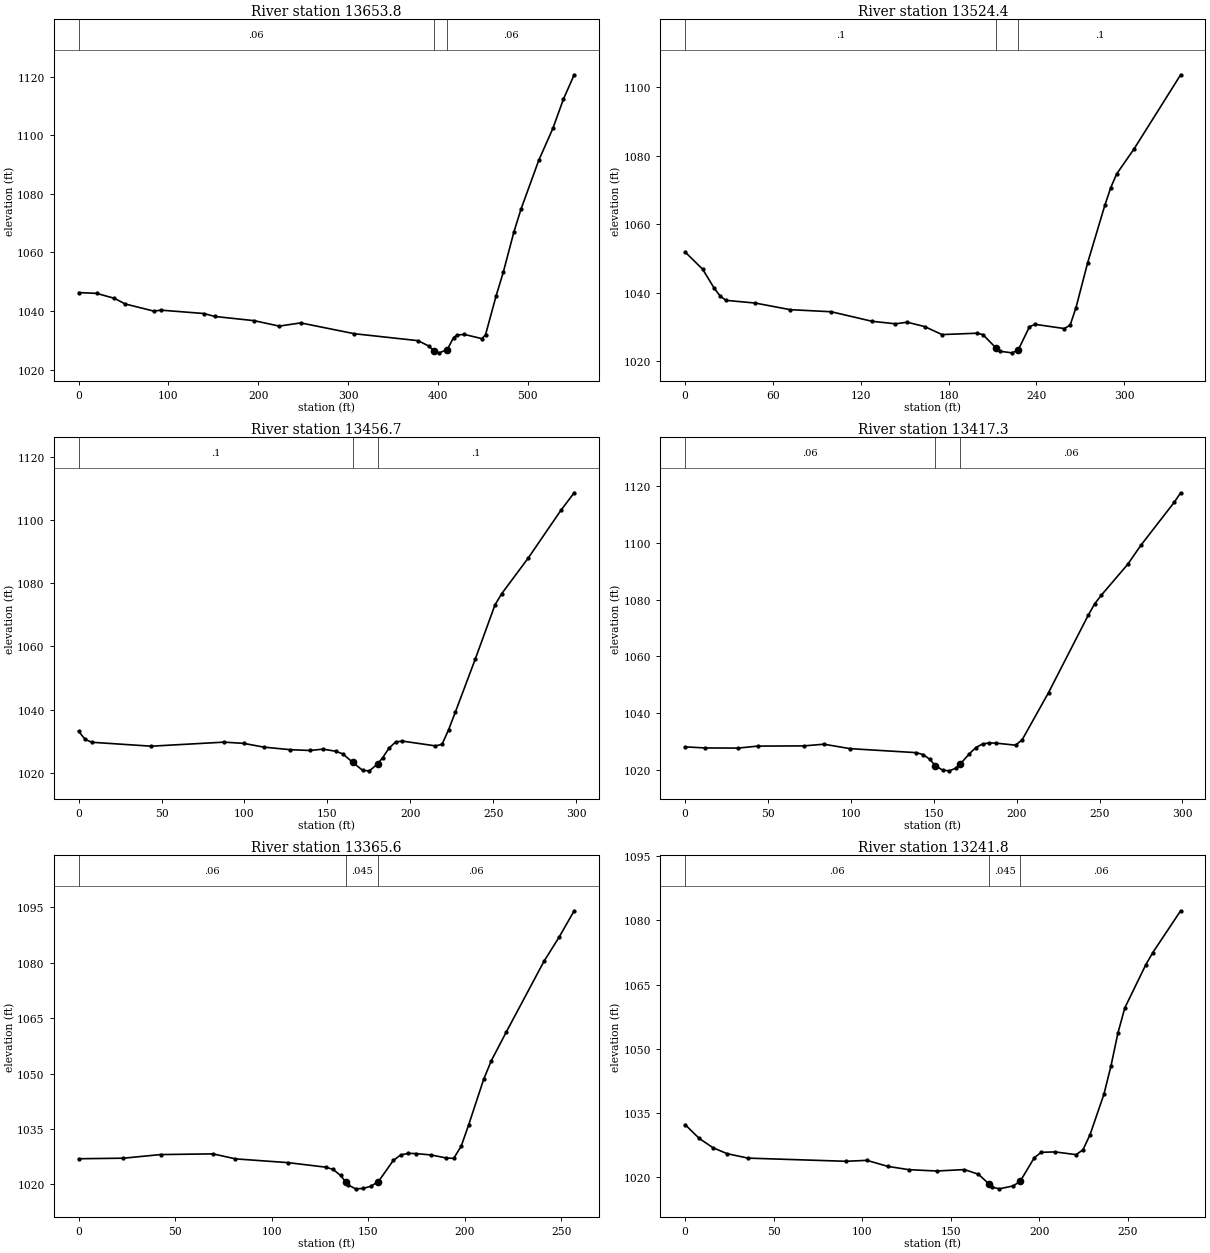
Type RM Length L Ch R = 1 ,13653.8 ,132.4,129.5,126.6
XS GIS Cut Line= 3
      1774697.53      364699.177     1774402.391      364704.602
     1774172.357      364818.535
#Sta/Elev= 30
       0 1046.27      20    1046    39.9  1044.3    51.9 1042.38    83.8 1039.94
    91.8 1040.27   139.6 1039.12   151.6 1038.12   195.5 1036.68   223.4 1034.82
   247.3 1035.92     307 1032.23   378.1 1029.85     390 1028.01   395.6 1026.38
   401.8  1025.7   410.6 1026.83   417.6 1030.92   421.6  1031.8   429.5 1031.99
   449.2 1030.54   453.2  1031.9     465 1045.18   472.9 1053.16   484.8 1066.99
   492.6 1074.67   512.4 1091.37   528.2 1102.33     540 1112.34   551.9 1120.61
#Mann= 3 , 0 , 0
       0     .06       0   395.6    .045       0   410.6     .06       0
Bank Sta=395.6,410.6
XS Rating Curve= 0 ,0
Exp/Cntr=0.3,0.1

Type RM Length L Ch R = 1 ,13524.4 ,68.7,67.7,66.7
XS GIS Cut Line= 3
     1774421.923      364535.332     1774290.629      364611.286
     1774130.039      364706.772
#Sta/Elev= 30
       0 1051.85      12 1046.82      20  1041.2      24 1038.98    27.9 1037.74
    47.9 1036.95    71.8 1035.02    99.8 1034.41   127.7 1031.63   143.7 1030.89
   151.7 1031.36   163.6 1030.09   175.5 1027.75   199.4 1028.15   203.4 1027.75
   212.5 1023.79   215.3 1022.87   223.2 1022.42   227.5  1023.2   235.2 1030.02
   239.1 1030.74     259 1029.51     263 1030.49     267 1035.58   274.9 1048.58
   286.8  1065.6   290.8 1070.67   294.8 1074.63   306.7 1081.95   338.5 1103.57
#Mann= 3 , 0 , 0
       0      .1       0   212.5    .045       0   227.5      .1       0
Bank Sta=212.5,227.5
XS Rating Curve= 0 ,0
Exp/Cntr=0.3,0.1

Type RM Length L Ch R = 1 ,13456.7 ,39.4,39.4,39.4
XS GIS Cut Line= 2
     1774342.712      364496.269     1774089.891      364655.774
#Sta/Elev= 30
       0 1033.11       4 1030.54       8 1029.66    43.8 1028.42    87.7  1029.7
    99.6 1029.31   111.6 1028.13   127.5 1027.32   139.5 1027.06   147.5 1027.49
   155.4 1026.78   159.4 1025.96   165.3 1023.32   171.4 1020.73   175.4 1020.62
   180.3 1022.77   183.4  1024.8   187.3 1027.86   191.3 1029.78   195.3 1030.03
   215.2 1028.52   219.2 1029.01   223.2 1033.68   227.2 1039.17   239.2 1055.92
   251.1 1073.08   255.1 1076.62     271 1087.82     291 1103.14   298.9 1108.61
#Mann= 3 , 0 , 0
       0      .1       0   165.3    .045       0   180.3      .1       0
Bank Sta=165.3,180.3
XS Rating Curve= 0 ,0
Exp/Cntr=0.3,0.1

Type RM Length L Ch R = 1 ,13417.3 ,53,51.7,50.4
XS GIS Cut Line= 2
      1774310.16      364470.227     1774057.339      364629.733
#Sta/Elev= 30
       0    1028      12 1027.61    31.9 1027.56    43.8 1028.26    71.7 1028.34
    83.7 1028.93    99.6 1027.36   139.5 1025.95   143.5 1025.27   147.5 1023.65
   150.9 1021.37   155.4 1019.75   159.4 1019.53   163.4 1020.51   165.9 1021.87
   171.4 1025.53   175.4 1027.76   179.4    1029   183.4 1029.38   187.3 1029.33
   199.3 1028.59   203.3 1030.48   219.2 1047.13   243.1  1074.4   247.1 1078.53
   251.1 1081.57     267 1092.46     275 1099.23     295 1114.32   298.9  1117.7
#Mann= 3 , 0 , 0
       0     .06       0   150.9    .045       0   165.9     .06       0
Bank Sta=150.9,165.9
XS Rating Curve= 0 ,0
Exp/Cntr=0.3,0.1

Type RM Length L Ch R = 1 ,13365.6 ,126,123.8,121.5
XS GIS Cut Line= 3
     1774271.098       364438.76     1774183.207      364487.588
     1774054.084      364575.479
#Sta/Elev= 30
       0 1026.96    23.2 1027.11    42.5 1028.09    69.6 1028.28    81.2 1026.93
   108.4 1025.91   127.9 1024.69   131.8 1024.08   135.7 1022.43   138.4 1020.65
   139.6 1019.86   143.5 1018.82   147.4 1018.93   151.3 1019.51   155.2 1020.72
     163  1026.5   166.9    1028   170.8 1028.41   174.7 1028.36   182.6 1027.98
   190.4 1027.17   194.3 1027.06   198.2 1030.39   202.1 1036.22   209.9 1048.57
   213.8  1053.5   221.6 1061.31   241.1  1080.4   248.9  1086.9   256.7 1094.03
#Mann= 3 , 0 , 0
       0     .06       0   138.4    .045       0   155.2     .06       0
Bank Sta=138.4,155.2
XS Rating Curve= 0 ,0
Exp/Cntr=0.3,0.1

Type RM Length L Ch R = 1 ,13241.8 ,90.6,89.7,88.7
XS GIS Cut Line= 3
     1774214.674      364312.892     1774132.209      364367.146
      1773988.98      364477.823
#Sta/Elev= 30
       0 1032.26     7.9 1029.05    15.8 1026.84    23.7 1025.46    35.5 1024.42
    90.8 1023.68   102.6  1023.9   114.4 1022.49   126.3 1021.72     142 1021.41
   157.7 1021.74   165.6 1020.64   171.4 1018.43   173.5 1017.62   177.4 1017.24
   185.3 1017.94   189.2 1019.05   197.1 1024.51     201 1025.78   208.9 1025.87
   220.7 1025.23   224.6 1026.38   228.6 1029.94   236.4 1039.35   240.4    1046
   244.3 1053.66   248.2 1059.55     260  1069.6     264 1072.48   279.7 1082.24
#Mann= 3 , 0 , 0
       0     .06       0   171.4    .045       0   189.2     .06       0
Bank Sta=171.4,189.2
XS Rating Curve= 0 ,0
Exp/Cntr=0.3,0.1

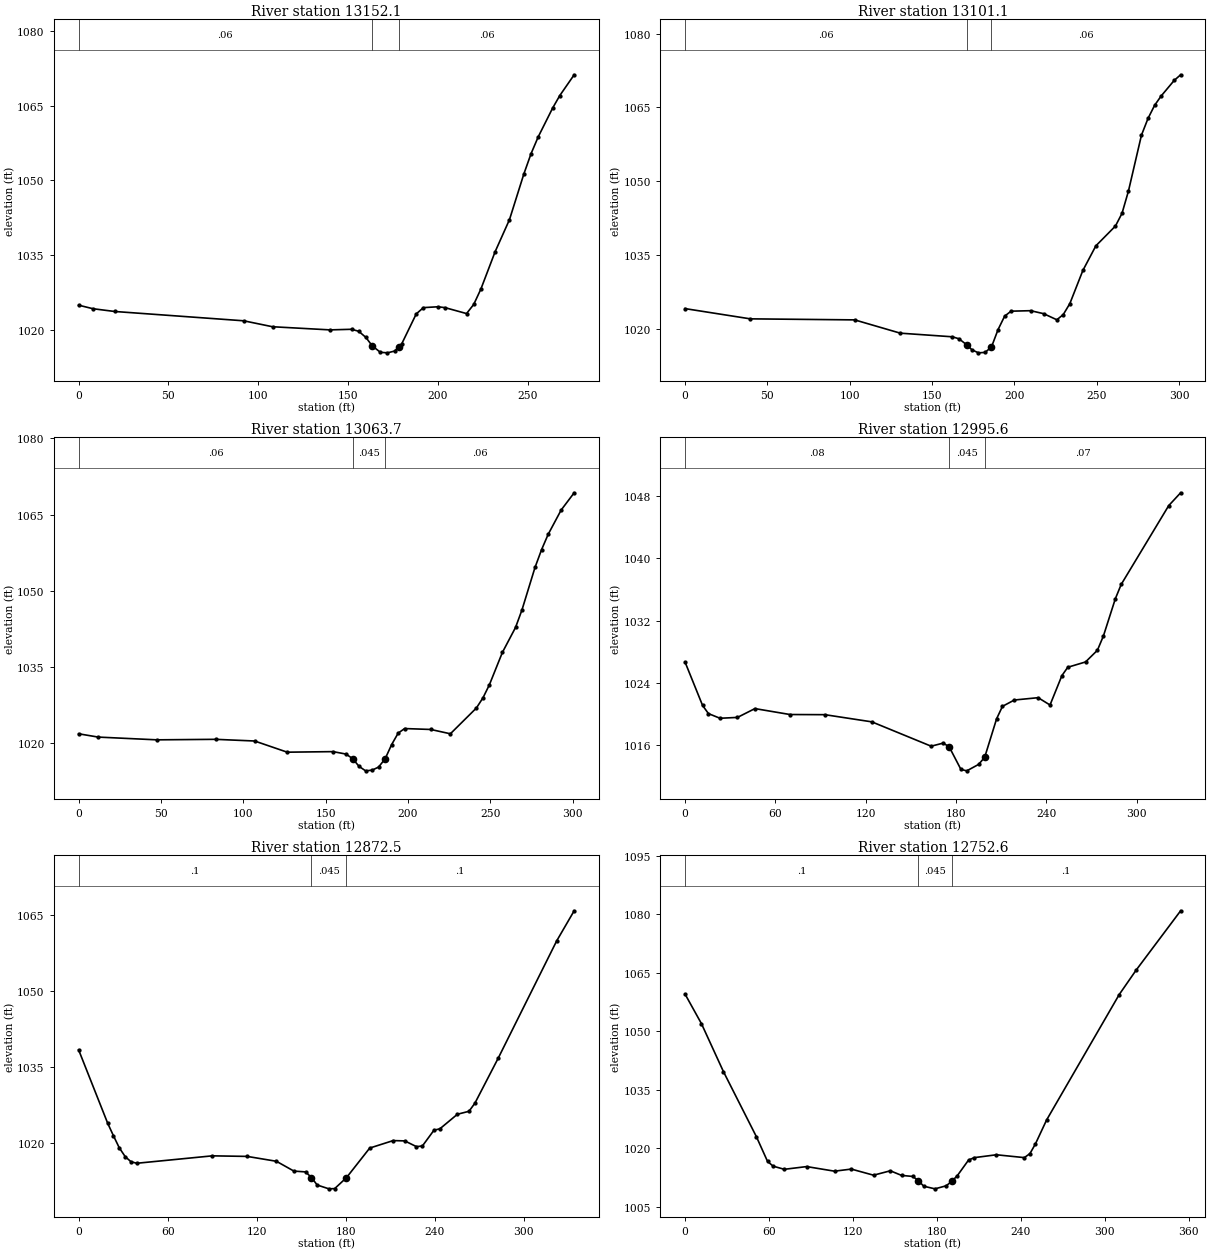
Type RM Length L Ch R = 1 ,13152.1 ,49.9,50.9,52
XS GIS Cut Line= 3
     1774138.719      364239.108     1774079.041      364292.276
     1773927.131      364415.974
#Sta/Elev= 30
       0 1024.99       8 1024.28      20 1023.73    91.9 1021.86   107.9 1020.67
   139.9 1020.04   151.9 1020.16   155.9 1019.76   159.9 1018.52   163.3 1016.89
   167.9 1015.55   171.9 1015.44   175.9  1015.8   178.3  1016.7   179.9  1017.3
   187.9 1023.24   191.9  1024.5   199.9 1024.67   203.9  1024.5   215.9 1023.31
   219.9 1025.14   223.9 1028.24   231.8  1035.7   239.8 1042.14   247.8 1051.29
   251.8 1055.35   255.8 1058.73   263.8 1064.48   267.8    1067   275.8 1071.16
#Mann= 3 , 0 , 0
       0     .06       0   163.3    .045       0   178.3     .06       0
Bank Sta=163.3,178.3
XS Rating Curve= 0 ,0
Exp/Cntr=0.3,0.1

Type RM Length L Ch R = 1 ,13101.1 ,37.5,37.4,37.5
XS GIS Cut Line= 2
     1774117.018      364202.215     1773878.303      364385.592
#Sta/Elev= 30
       0 1024.08    39.6    1022     103 1021.79   130.7 1019.09   162.4 1018.35
   166.4 1017.94   171.1 1016.71   174.3 1015.69   178.2 1015.09   182.2 1015.18
   186.1 1016.28   190.1 1019.82   194.1 1022.55     198 1023.56   209.9 1023.66
   217.8 1023.05   225.8 1021.81   229.7 1022.87   233.7  1025.1   241.6 1031.83
   249.5 1036.84   261.4 1040.87   265.4 1043.46   269.3 1047.98   277.2 1059.34
   281.2 1062.76   285.2 1065.41   289.1 1067.28   297.1 1070.48     301 1071.62
#Mann= 3 , 0 , 0
       0     .06       0   171.1    .045       0   186.1     .06       0
Bank Sta=171.1,186.1
XS Rating Curve= 0 ,0
Exp/Cntr=0.3,0.1

Type RM Length L Ch R = 1 ,13063.7 ,70.3,68.1,66.3
XS GIS Cut Line= 2
     1774090.976      364175.088     1773852.261      364358.465
#Sta/Elev= 30
       0 1021.89    11.9 1021.24    47.5  1020.7    83.2  1020.8   106.9 1020.47
   126.7 1018.27   154.5 1018.38   162.4  1017.9   166.4 1017.01   170.3 1015.49
   174.3  1014.6   178.2 1014.73   182.2 1015.34   186.2 1016.98   190.1 1019.75
   194.1 1022.02     198 1022.92   213.9 1022.74   225.8 1021.89   241.6 1026.96
   245.6 1028.96   249.5 1031.53   257.4  1037.9   265.4 1042.82   269.3 1046.27
   277.2 1054.61   281.2 1058.12   285.2 1061.13   293.1 1065.92     301 1069.31
#Mann= 3 , 0 , 0
       0     .06       0   166.4    .045       0   186.2     .06       0
Bank Sta=166.4,186.2
XS Rating Curve= 0 ,0
Exp/Cntr=0.3,0.1

Type RM Length L Ch R = 1 ,12995.6 ,121.4,123.1,124.5
XS GIS Cut Line= 3
      1774066.02      364123.005     1773968.364      364178.344
     1773803.433      364319.403
#Sta/Elev= 30
       0 1026.67    11.6 1021.13    15.5 1020.08    23.2 1019.48    34.8 1019.59
    46.4 1020.72    69.7 1019.96    92.9 1019.94   124.1 1019.02   163.5  1015.9
   171.4 1016.29   175.4 1015.85   183.3 1012.92   187.2 1012.74   195.1 1013.57
   199.1 1014.49     207 1019.41   210.9 1021.01   218.8 1021.82   234.6 1022.12
   242.5 1021.18   250.4 1024.95   254.3 1026.02   266.1  1026.7     274  1028.2
     278 1030.04   285.9  1034.8   289.8 1036.64   321.4 1046.75   329.3 1048.39
#Mann= 3 , 0 , 0
       0     .08       0   175.4    .045       0   199.1     .07       0
Bank Sta=175.4,199.1
XS Rating Curve= 0 ,0
Exp/Cntr=0.3,0.1

Type RM Length L Ch R = 1 ,12872.5 ,120.2,119.9,119.5
XS GIS Cut Line= 3
     1773972.704      364014.498     1773881.558      364094.793
     1773714.457      364226.087
#Sta/Elev= 30
       0 1038.39    19.6 1023.95    23.5 1021.48    27.4 1019.13    31.4 1017.39
    35.3 1016.39    39.2 1016.09    90.1 1017.55   113.6 1017.44   133.3 1016.48
   145.1 1014.55     153 1014.39   156.9 1013.29   160.8 1011.81   168.7 1011.06
   172.6 1011.11   180.5 1013.25   196.2 1019.08     212 1020.55   219.8 1020.49
   227.7 1019.36   231.7 1019.49   239.5 1022.59   243.5 1022.87   255.3 1025.73
   263.1 1026.31   267.1 1027.91   282.8 1036.76   322.2 1059.82     334 1065.75
#Mann= 3 , 0 , 0
       0      .1       0   156.9    .045       0   180.5      .1       0
Bank Sta=156.9,180.5
XS Rating Curve= 0 ,0
Exp/Cntr=0.3,0.1

Type RM Length L Ch R = 1 ,12752.6 ,159.7,158.1,156.3
XS GIS Cut Line= 3
     1773915.195      363912.502     1773879.388      363942.884
     1773639.587      364134.941
#Sta/Elev= 30
       0 1059.52    11.7 1051.95    27.4 1039.66      51 1022.93    58.9 1016.64
    62.9  1015.4    70.9 1014.59    86.9 1015.29   106.8 1014.11   118.8 1014.65
   134.7 1013.08   146.7 1014.21   154.7 1013.03   162.7 1012.76   166.7 1011.69
   170.6 1010.25   178.6 1009.58   186.6 1010.36   190.6  1011.5   194.6 1012.97
   202.6 1016.96   206.6 1017.58   222.5 1018.32   242.5 1017.59   246.5 1018.63
   250.4  1021.1   258.4 1027.25   310.3 1059.43   322.3 1065.65   354.2 1080.92
#Mann= 3 , 0 , 0
       0      .1       0   166.7    .045       0   190.6      .1       0
Bank Sta=166.7,190.6
XS Rating Curve= 0 ,0
Exp/Cntr=0.3,0.1