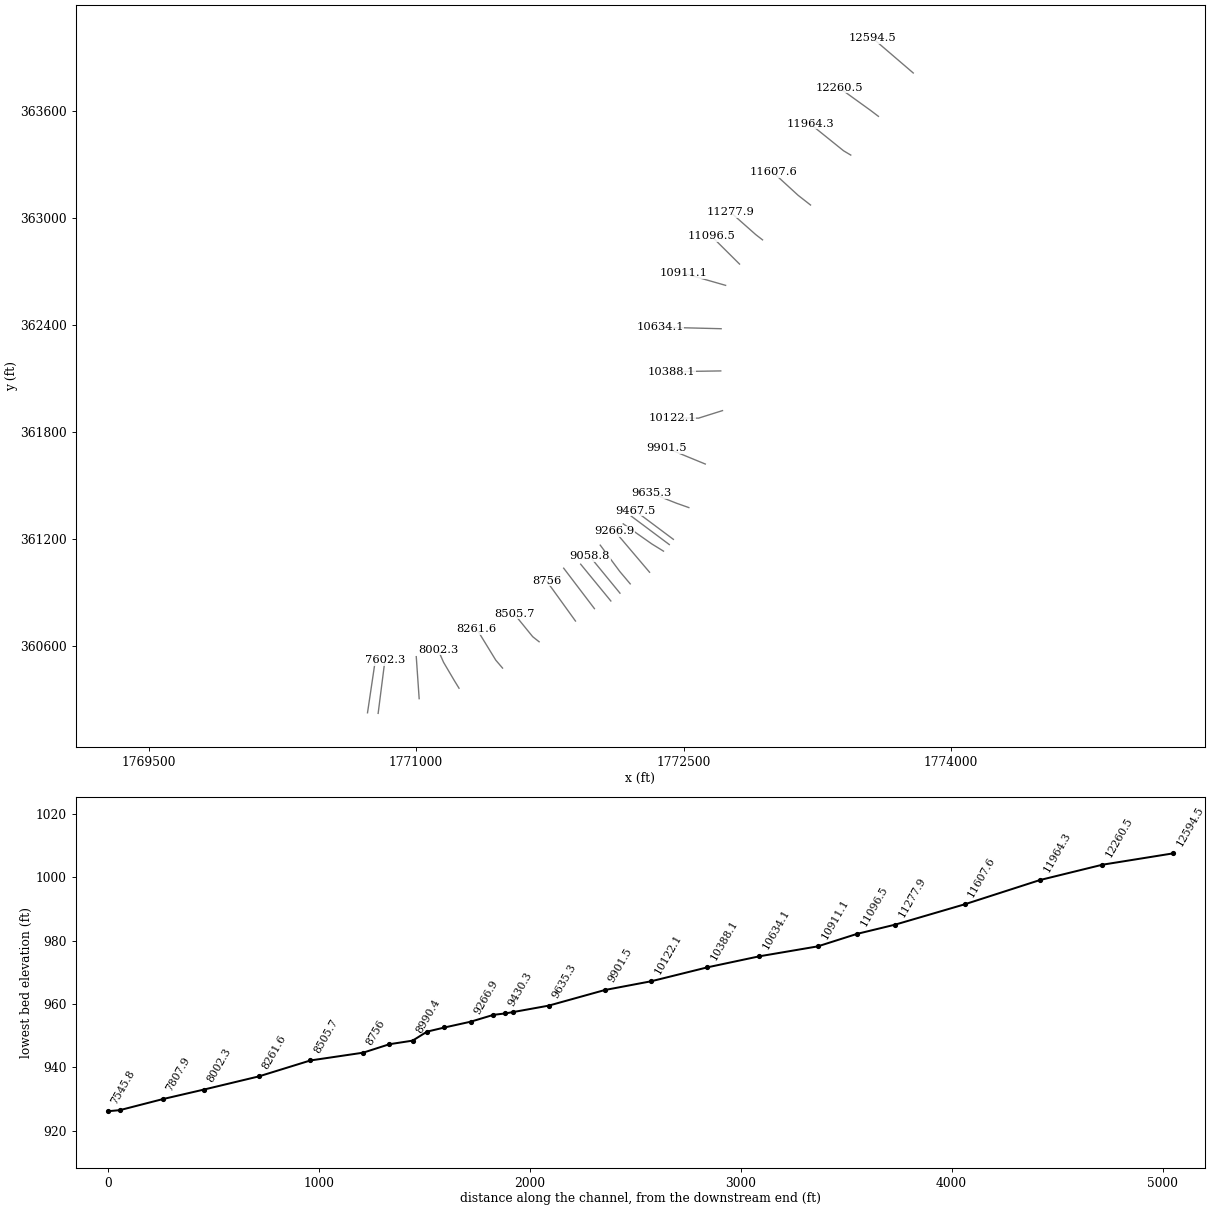
HEC-RAS study WHITESBR.prj: WHITESBR

--- WHITESBR.g01 (geometry) --- (continued)

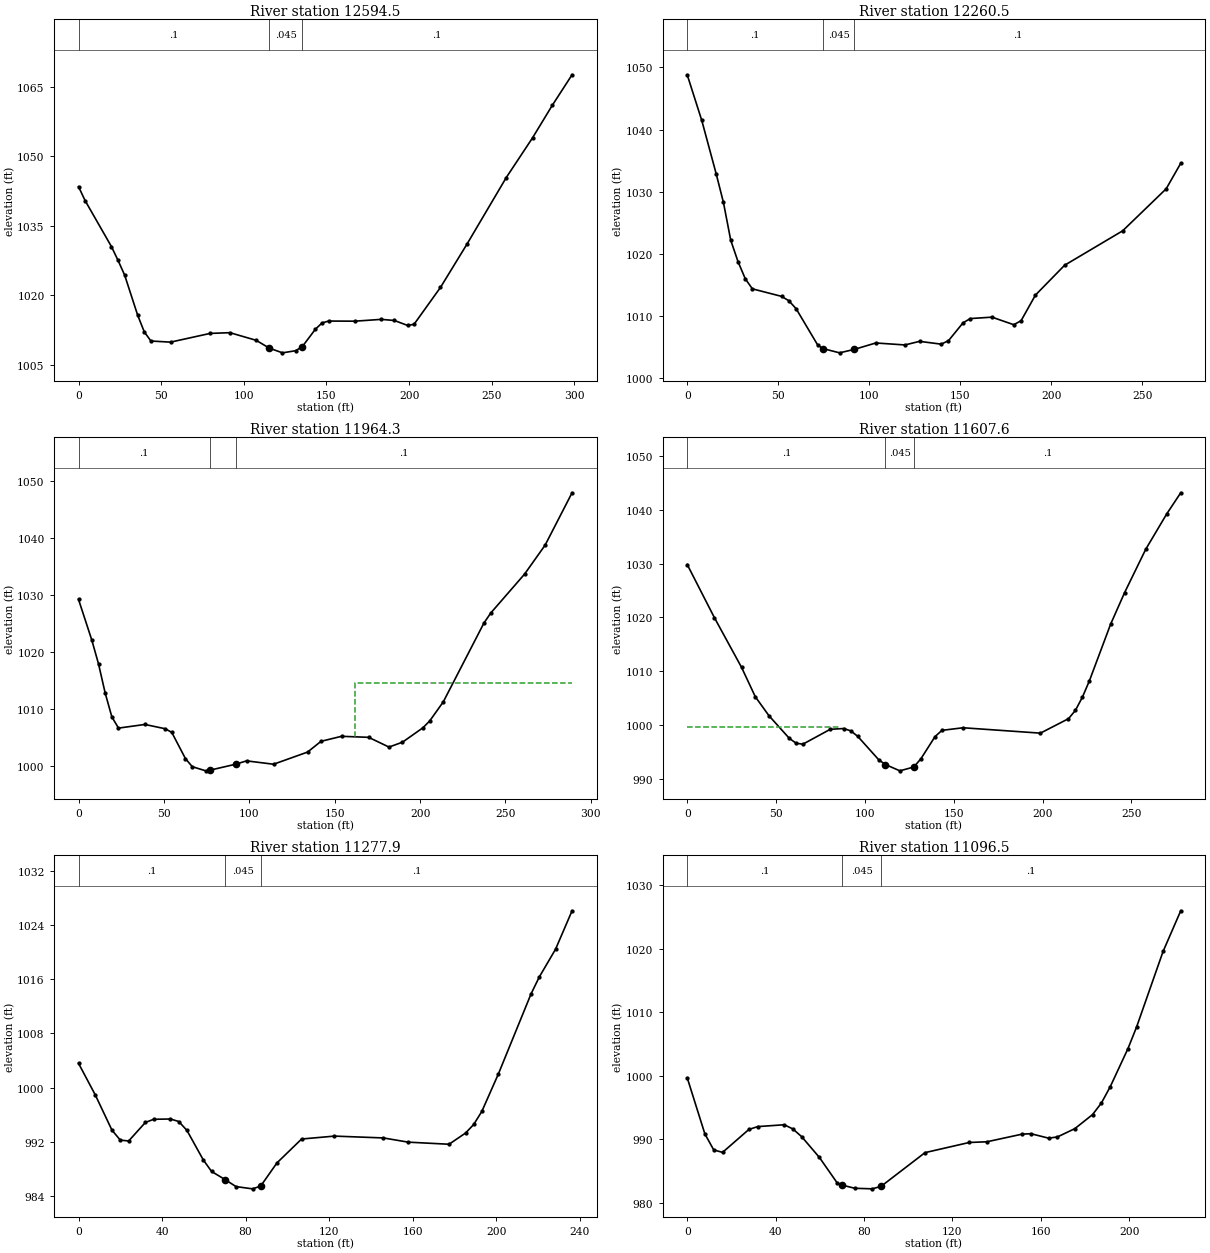
Type RM Length L Ch R = 1 ,12594.5 ,330.1,334,339.1
XS GIS Cut Line= 2
     1773788.242      363810.505     1773561.462      364004.733
#Sta/Elev= 30
       0 1043.44       4 1040.42    19.9 1030.52    23.9 1027.54    27.9 1024.36
    35.8 1015.69    39.8  1012.1    43.8 1010.14    55.7  1009.9    79.6 1011.78
    91.6 1011.94   107.5 1010.29   115.4 1008.61   123.4 1007.59   131.4 1008.05
   135.4 1008.94   143.3 1012.68   147.3 1014.03   151.3 1014.45   167.2 1014.42
   183.1 1014.81   191.1 1014.57   199.1  1013.5     203 1013.75     219 1021.71
   234.9 1030.97   258.8 1045.41   274.7 1053.98   286.6 1060.97   298.6 1067.58
#Mann= 3 , 0 , 0
       0      .1       0   115.4    .045       0   135.4      .1       0
Bank Sta=115.4,135.4
XS Rating Curve= 0 ,0
Exp/Cntr=0.3,0.1

Type RM Length L Ch R = 1 ,12260.5 ,296.6,296.2,291.3
XS GIS Cut Line= 3
     1773592.929       363567.45     1773548.442      363601.087
     1773373.745      363726.955
#Sta/Elev= 30
       0 1048.82       8 1041.46    15.9 1032.88    19.9 1028.25    23.9 1022.17
    27.9 1018.72    31.9 1015.95    35.8 1014.33    51.8 1013.12    55.8 1012.42
    59.8 1011.14    71.7 1005.27    74.6  1004.7    83.7 1004.02    91.7 1004.57
   103.6 1005.61   119.6 1005.29   127.6 1005.87   139.5 1005.42   143.5 1005.97
   151.5 1008.85   155.5 1009.54   167.4 1009.77   179.4 1008.55   183.4  1009.2
   191.3 1013.33   207.3 1018.13   239.2 1023.68   263.1 1030.45   271.1 1034.56
#Mann= 3 , 0 , 0
       0      .1       0    74.6    .045       0    91.7      .1       0
Bank Sta=74.6,91.7
XS Rating Curve= 0 ,0
Exp/Cntr=0.3,0.1

Type RM Length L Ch R = 1 ,11964.3 ,358,356.7,353.9
XS GIS Cut Line= 3
     1773437.765      363350.436     1773397.617      363374.307
     1773208.815      363526.217
#Sta/Elev= 30
       0 1029.26     7.8  1022.1    11.7 1017.95    15.6 1012.84    19.5 1008.66
    23.4 1006.68    38.9 1007.32    50.7 1006.57    54.6 1005.93    62.6 1001.33
    66.6  999.91    74.5  999.18      77   999.3      92 1000.34    98.4 1000.93
   114.2 1000.34   134.1 1002.47     142 1004.36     154 1005.24   169.9 1005.06
   181.8 1003.35   189.7 1004.21   201.6 1006.72   205.6 1007.92   213.6 1011.29
   237.4 1025.12   241.4 1026.88   261.2 1033.71   273.2 1038.78     289 1047.98
#Mann= 3 , 0 , 0
       0      .1       0      77    .045       0      92      .1       0
#XS Ineff= 2 , 0
                          161.82         1014.57
Permanent Ineff=
       F       F
Bank Sta=77,92
XS Rating Curve= 0 ,0
Exp/Cntr=0.3,0.1

Type RM Length L Ch R = 1 ,11607.6 ,327.5,329.6,328.3
XS GIS Cut Line= 3
      1773212.07      363070.488     1773142.626      363124.741
     1773002.652      363252.779
#Sta/Elev= 30
       0 1029.84    15.3 1019.97    30.6 1010.73    38.3  1005.3      46 1001.76
    57.5  997.55    61.3  996.65    65.1  996.47    80.5  999.23    88.1  999.38
    92.1  998.94      96  997.92   107.9  993.54   111.6  992.69   119.7  991.52
   127.6  992.24   131.6  993.79   139.5  997.88   143.4  999.04   155.3  999.52
   198.8  998.52   214.6  1001.2   218.5 1002.74   222.5 1005.24   226.4 1008.25
   238.3 1018.73   246.2 1024.62   258.1 1032.67   269.9 1039.23   277.8 1043.16
#Mann= 3 , 0 , 0
       0      .1       0   111.6    .045       0   127.6      .1       0
#XS Ineff= 2 , 0
           85.56  999.72
Permanent Ineff=
       F       F
Bank Sta=111.6,127.6
XS Rating Curve= 0 ,0
Exp/Cntr=0.3,0.1

Type RM Length L Ch R = 1 ,11277.9 ,183.8,181.4,178.7
XS GIS Cut Line= 3
     1772942.973      362875.175     1772904.995      362904.472
     1772763.936      363029.255
#Sta/Elev= 30
       0 1003.59       8  998.95      16  993.75      20  992.28      24  992.15
      32  994.88      36  995.35      44  995.39      48  995.02    51.9  993.71
    59.7  989.38    63.7  987.66    70.2  986.46    75.4  985.43    83.3   985.1
    87.2   985.5      95  988.92   106.8  992.44   122.5  992.87     146   992.6
   157.8  991.98   177.4  991.67   185.3  993.32   189.2  994.58   193.1  996.51
     201 1002.01   216.7 1013.85   220.6 1016.31   228.4 1020.41   236.3 1026.07
#Mann= 3 , 0 , 0
       0      .1       0    70.2    .045       0    87.2      .1       0
Bank Sta=70.2,87.2
XS Rating Curve= 0 ,0
Exp/Cntr=0.3,0.1

Type RM Length L Ch R = 1 ,11096.5 ,165.7,185.4,203.7
XS GIS Cut Line= 2
      1772813.85      362739.542     1772655.429      362896.877
#Sta/Elev= 30
       0  999.66       8  990.81      12   988.3      16  987.91    27.9  991.52
    31.9  991.97    43.9  992.26    47.8   991.6    51.8  990.38    59.8  987.12
    67.8  983.13    70.2  982.75    75.8  982.26    83.7  982.17    87.7  982.56
   107.6  987.87   127.6  989.47   135.6  989.58   151.5  990.78   155.5  990.85
   163.5  990.15   167.5  990.34   175.4  991.65   183.4  993.86   187.4  995.68
   191.4  998.25   199.4 1004.23   203.3 1007.63   215.3 1019.54   223.3 1025.95
#Mann= 3 , 0 , 0
       0      .1       0    70.2    .045       0    87.7      .1       0
Bank Sta=70.2,87.7
XS Rating Curve= 0 ,0
Exp/Cntr=0.3,0.1

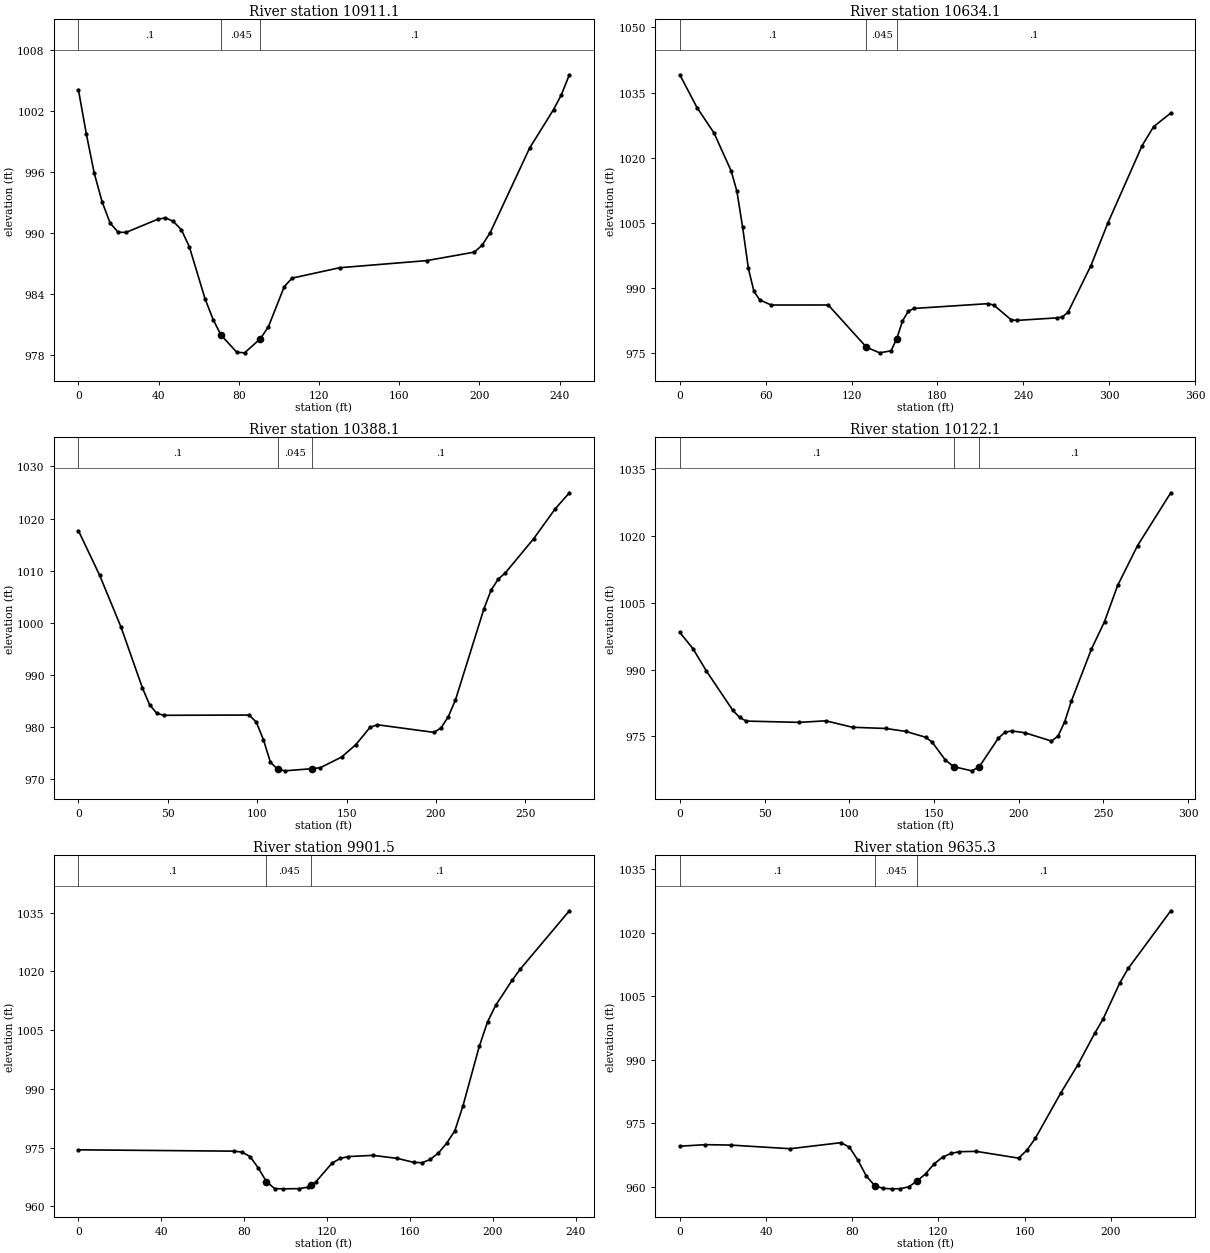
Type RM Length L Ch R = 1 ,10911.1 ,267.6,277.1,286.6
XS GIS Cut Line= 2
     1772735.725      362620.184     1772500.265      362687.458
#Sta/Elev= 30
       0 1004.06       4  999.67     7.9  995.87    11.8  993.07    15.8  990.98
    19.8  990.08    23.7  990.05    39.5  991.34    43.4  991.49    47.4  991.13
    51.4   990.3    55.3  988.67    63.2  983.53    67.2  981.51    71.1  979.99
      79   978.3    82.9  978.24    90.8  979.63    94.8  980.81   102.7  984.74
   106.6  985.57   130.3  986.59   173.8  987.29   197.5  988.12   201.4   988.8
   205.4  990.03   225.1  998.34     237  1002.1   240.9 1003.55   244.9 1005.52
#Mann= 3 , 0 , 0
       0      .1       0    71.1    .045       0    90.8      .1       0
Bank Sta=71.1,90.8
XS Rating Curve= 0 ,0
Exp/Cntr=0.3,0.1

Type RM Length L Ch R = 1 ,10634.1 ,244.1,246,247.5
XS GIS Cut Line= 2
     1772710.768      362377.128     1772367.886      362385.809
#Sta/Elev= 30
       0 1039.08      12 1031.54    23.9 1025.69    35.9 1016.93    39.9 1012.24
    43.9 1003.97    47.9  994.51    51.8  989.24    55.8   987.3    63.8   986.1
   103.7  986.11   130.4  976.39   139.6   975.1   147.6  975.57   151.6  978.38
   155.5  982.37   159.5  984.62   163.5  985.31   215.4  986.42   219.4  986.08
   231.3  982.75   235.3  982.56   263.2  983.14   267.2  983.35   271.2  984.43
   287.2  995.16   299.1 1005.01     323 1022.79     331 1027.14     343 1030.27
#Mann= 3 , 0 , 0
       0      .1       0   130.4    .045       0   151.6      .1       0
Bank Sta=130.4,151.6
XS Rating Curve= 0 ,0
Exp/Cntr=0.3,0.1

Type RM Length L Ch R = 1 ,10388.1 ,263.7,266,264.6
XS GIS Cut Line= 2
     1772708.598      362140.583     1772434.075      362136.243
#Sta/Elev= 30
       0 1017.68    11.9 1009.11    23.9  999.13    35.8  987.52    39.8  984.32
    43.8  982.66    47.8  982.27    95.5  982.32    99.5  980.96   103.5  977.58
   107.4  973.27   111.4  971.94   115.4  971.62   130.5  972.03   135.3  972.22
   147.2  974.26   155.2  976.65   163.1  979.95   167.1  980.46     199  978.99
   202.9   979.9   206.9     982   210.9  985.22   226.8 1002.66   230.8 1006.25
   234.8 1008.38   238.8 1009.58   254.7 1016.16   266.6 1021.82   274.6 1024.94
#Mann= 3 , 0 , 0
       0      .1       0   111.4    .045       0   130.5      .1       0
Bank Sta=111.4,130.5
XS Rating Curve= 0 ,0
Exp/Cntr=0.3,0.1

Type RM Length L Ch R = 1 ,10122.1 ,238.1,220.7,206.3
XS GIS Cut Line= 3
     1772718.364      361918.144     1772583.815      361875.826
      1772435.16      361876.911
#Sta/Elev= 30
       0  998.33     7.8  994.66    15.7  989.65    31.3  980.81    35.3  979.23
    39.2  978.41    70.5  978.12    86.2  978.47   101.9  977.02   121.5  976.75
   133.2   976.1     145  974.79   148.9  973.68   156.7  969.64   161.7  968.16
   172.3  967.23   176.7  968.15     188   974.6   191.9   975.9   195.8   976.2
   203.6  975.79   219.3  973.92   223.2  975.05   227.1  978.25     231  982.85
   242.8  994.51   250.6 1000.76   258.4 1008.93   270.1 1017.84   289.7 1029.71
#Mann= 3 , 0 , 0
       0      .1       0   161.7    .045       0   176.7      .1       0
Bank Sta=161.7,176.7
XS Rating Curve= 0 ,0
Exp/Cntr=0.3,0.1

Type RM Length L Ch R = 1 ,9901.5  ,265.1,266.2,266.5
XS GIS Cut Line= 2
     1772621.792      361618.665     1772402.608      361708.726
#Sta/Elev= 30
       0  974.42      75  974.08      79  973.83    82.9  972.68    86.9  969.72
    90.8  966.27    94.8   964.5    98.7  964.45   106.6   964.5   110.6  964.86
   112.1  965.36   114.5  966.16   122.4     971   126.4  972.22   130.3   972.7
   142.2     973     154  972.23   161.9  971.21   165.9  971.12   169.8  971.95
   173.8   973.6   177.7  976.06   181.7  979.26   185.6  985.57   193.5 1000.83
   197.5  1007.1   201.4 1011.31   209.3 1017.69   213.3 1020.59     237  1035.5
#Mann= 3 , 0 , 0
       0      .1       0    90.8    .045       0   112.1      .1       0
Bank Sta=90.8,112.1
XS Rating Curve= 0 ,0
Exp/Cntr=0.3,0.1

Type RM Length L Ch R = 1 ,9635.3  ,178.2,167.8,158
XS GIS Cut Line= 3
     1772529.561      361374.524     1772459.032      361399.481
     1772316.888      361455.904
#Sta/Elev= 30
       0  969.59    11.8  969.96    23.6  969.86    51.2     969    74.8  970.43
    78.7  969.35    82.7  966.23    86.6  962.48    90.5  960.25    94.4  959.62
    98.3  959.52   102.3  959.56   106.2  959.99   110.1  961.38     114  963.06
     118  965.41   121.9  967.01   125.8  967.88   129.7   968.3   137.6  968.37
   157.2  966.77   161.1  968.68     165   971.5   176.8  982.21   184.6  988.74
   192.5  996.26   196.4  999.65   204.2 1008.23   208.1 1011.63   227.8 1025.22
#Mann= 3 , 0 , 0
       0      .1       0    90.5    .045       0   110.1      .1       0
Bank Sta=90.5,110.1
XS Rating Curve= 0 ,0
Exp/Cntr=0.3,0.1

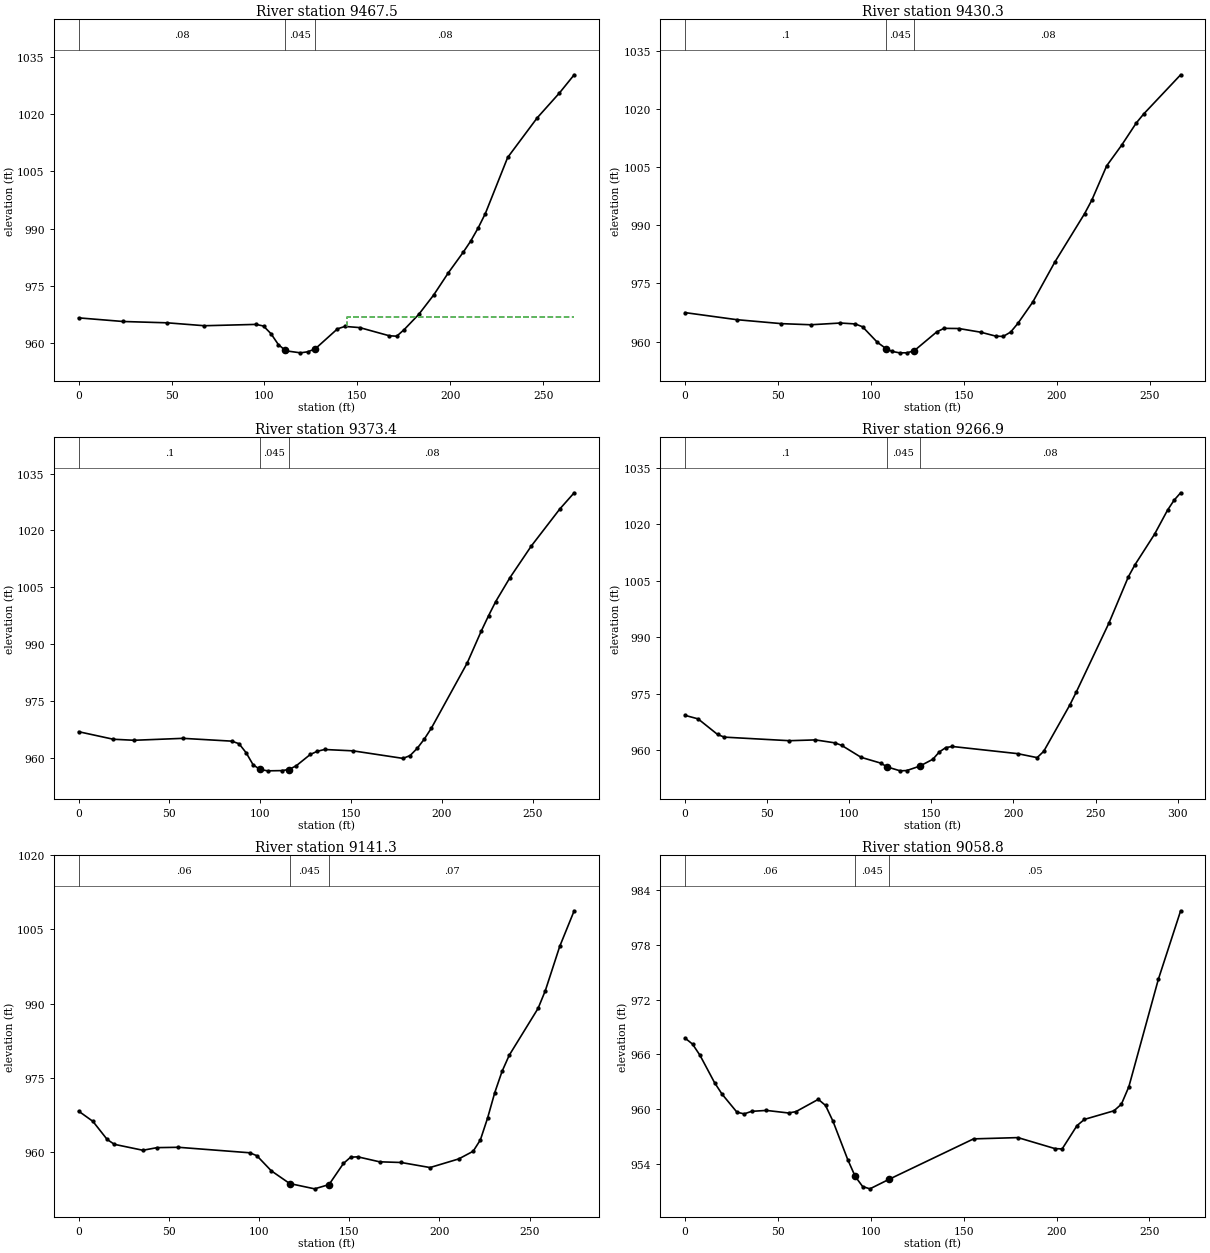
Type RM Length L Ch R = 1 ,9467.5  ,37.2,37.2,37.2
XS GIS Cut Line= 2
     1772442.756      361196.573     1772228.997      361356.078
#Sta/Elev= 30
       0  966.66    23.9  965.71    47.8  965.36    67.7   964.6    95.5  964.95
    99.5  964.52   103.5  962.53   107.5  959.66   110.8  958.32   111.5  958.03
   119.4   957.5   123.4  957.78   127.4  958.57   139.3  963.78   143.3  964.42
   151.3  964.11   167.2  961.97   171.2  961.86   175.2  963.58   183.1   967.6
   191.1  972.66     199  978.48     207  983.86     211  986.76     215  990.19
   218.9  993.99   230.9 1008.67   246.8 1019.05   258.8 1025.58   266.7 1030.33
#Mann= 3 , 0 , 0
       0     .08       0   110.8    .045       0   127.4     .08       0
#XS Ineff= 2 , 0
                          144.55          966.76
Permanent Ineff=
       F       F
Bank Sta=110.8,127.4
XS Rating Curve= 0 ,0
Exp/Cntr=0.3,0.1

Type RM Length L Ch R = 1 ,9430.3  ,55.4,56.9,58
XS GIS Cut Line= 2
     1772419.969      361167.276     1772206.211      361326.781
#Sta/Elev= 30
       0  967.47    27.9  965.64    51.8  964.62    67.7  964.33    83.6  964.78
    91.6  964.54    95.5  963.81   103.5  959.78   108.3  958.11   111.5  957.43
   115.4  957.07   119.4  957.08   123.3  957.61   135.4  962.47   139.3   963.4
   147.3  963.36   159.2   962.4   167.2  961.39   171.2  961.31   175.2  962.44
   179.1  964.68   187.1  970.19     199  980.55     215  993.05   218.9  996.56
   226.9 1005.43   234.9 1010.73   242.8 1016.49   246.8 1018.83   266.7 1028.97
#Mann= 3 , 0 , 0
       0      .1       0   108.3    .045       0   123.3     .08       0
Bank Sta=108.3,123.3
XS Rating Curve= 0 ,0
Exp/Cntr=0.3,0.1

Type RM Length L Ch R = 1 ,9373.4  ,116.5,106.5,96.9
XS GIS Cut Line= 3
     1772387.417      361130.384     1772322.313      361170.531
     1772161.723      361283.378
#Sta/Elev= 30
       0  966.93    19.1  964.94    30.6  964.67    57.4  965.18    84.3  964.44
    88.3  963.76    92.2  961.39    96.1  958.17    99.9  956.98     104  956.61
   111.8  956.67   115.7  956.96   119.7  957.91   127.5  960.92   131.4  961.77
   135.4  962.24   151.1  961.88   178.6  959.89   182.5  960.65   186.4  962.55
   190.3  964.99   194.2  967.88   213.9  985.04   221.7  993.52   225.7  997.55
   229.6 1001.25   237.4 1007.52   249.2  1015.9   264.9 1025.67   272.8 1029.94
#Mann= 3 , 0 , 0
       0      .1       0    99.9    .045       0   115.7     .08       0
Bank Sta=99.9,115.7
XS Rating Curve= 0 ,0
Exp/Cntr=0.3,0.1

Type RM Length L Ch R = 1 ,9266.9  ,127.9,125.6,123.1
XS GIS Cut Line= 2
     1772309.292      361012.111      1772113.98      361242.146
#Sta/Elev= 30
       0  969.21     7.9  968.28    19.8  964.13    23.8  963.43    63.5  962.48
    79.4  962.69    91.3   961.9    95.3  961.25   107.2  958.06   119.1  956.53
   123.1   955.5     131  954.47     135  954.55   142.9  955.72   150.9  957.55
   154.8  959.48   158.8  960.66   162.8  960.94   202.5  959.04   214.4  957.98
   218.4  959.65   234.3  971.96   238.2  975.37   258.1  993.71     270 1006.07
     274 1009.24   285.9 1017.34   293.8 1023.73   297.8 1026.38   301.8 1028.36
#Mann= 3 , 0 , 0
       0      .1       0   123.1    .045       0   142.9     .08       0
Bank Sta=123.1,142.9
XS Rating Curve= 0 ,0
Exp/Cntr=0.3,0.1

Type RM Length L Ch R = 1 ,9141.3  ,80.2,82.5,83.8
XS GIS Cut Line= 3
     1772200.785      360947.007     1772142.192      361016.451
       1772032.6      361164.021
#Sta/Elev= 30
       0  968.31     7.9  966.25    15.8   962.6    19.8  961.61    35.6  960.41
    43.5  960.94    55.3  961.01    94.9   959.9    98.8  959.31   106.8  956.26
     117  953.69   130.8  952.62   138.8  953.48   146.8  957.75   150.8  959.02
   154.8  959.08   166.8  958.08   178.8  957.94   194.8  956.92   210.7  958.66
   218.7  960.21   222.7   962.5   226.7  966.91   230.7  972.07   234.7  976.32
   238.7   979.6   254.7  989.07   258.7  992.63   266.7 1001.59   274.7 1008.77
#Mann= 3 , 0 , 0
       0     .06       0     117    .045       0   138.8     .07       0
Bank Sta=117,138.8
XS Rating Curve= 0 ,0
Exp/Cntr=0.3,0.1

Type RM Length L Ch R = 1 ,9058.8  ,68.5,68.4,68.3
XS GIS Cut Line= 2
     1772143.277      360894.924     1771974.006      361101.087
#Sta/Elev= 30
       0  967.78       4  967.13       8  965.91    15.9   962.9    19.9  961.66
    27.9  959.69    31.8   959.5    35.8  959.78    43.8  959.88    55.7   959.6
    59.7  959.75    71.7  961.09    75.6  960.43    79.6  958.71    87.6  954.49
    91.6  952.66    95.6  951.56    99.5  951.31   109.8  952.35   155.3  956.77
   179.2  956.91   199.1  955.71     203  955.67     211  958.22     215   958.9
   230.9  959.84   234.9  960.56   238.9  962.46   254.8  974.21   266.8   981.7
#Mann= 3 , 0 , 0
       0     .06       0    91.6    .045       0   109.8     .05       0
Bank Sta=91.6,109.8
XS Rating Curve= 0 ,0
Exp/Cntr=0.3,0.1

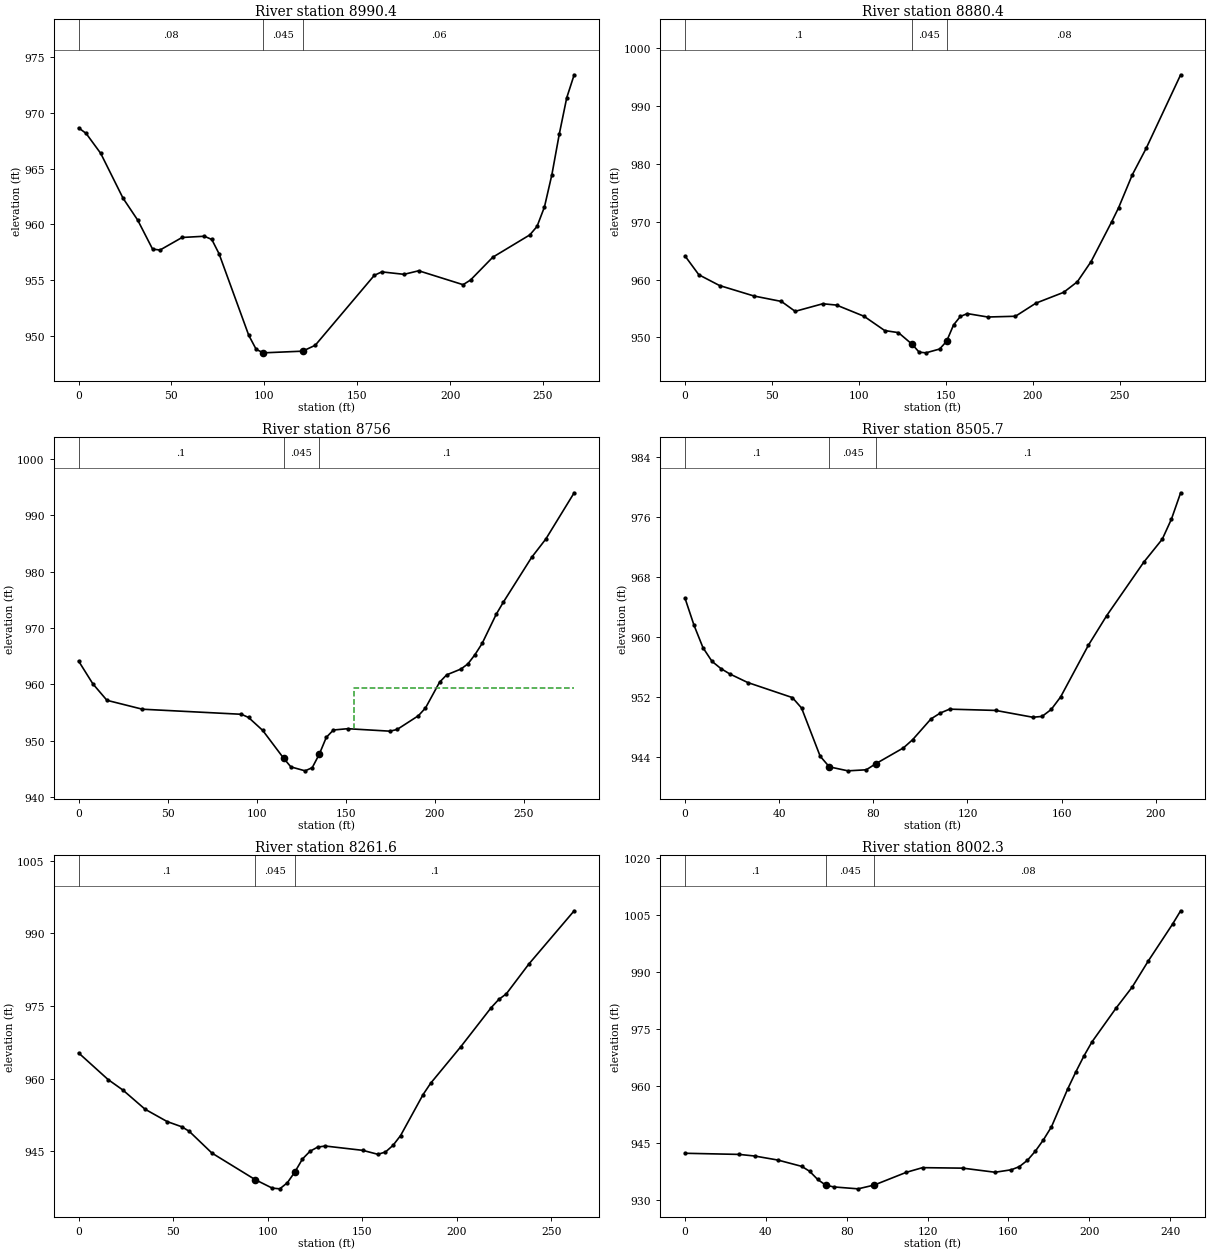
Type RM Length L Ch R = 1 ,8990.4  ,107.7,110,109
XS GIS Cut Line= 2
     1772092.061      360851.087     1771922.791       361057.25
#Sta/Elev= 30
       0  968.67       4  968.18    11.9  966.38    23.9  962.36    31.8  960.39
    39.8  957.79    43.8   957.7    55.7  958.83    67.7  958.94    71.7  958.65
    75.6  957.37    91.6  950.04    95.6  948.78    99.5  948.47   120.6  948.62
   127.4  949.15   159.2  955.43   163.2  955.74   175.2  955.52   183.1  955.84
     207  954.59     211  955.01     223  957.06   242.9  959.06   246.8  959.82
   250.8  961.57   254.8  964.47   258.8  968.13   262.8  971.38   266.8  973.44
#Mann= 3 , 0 , 0
       0     .08       0    99.5    .045       0   120.6     .06       0
Bank Sta=99.5,120.6
XS Rating Curve= 0 ,0
Exp/Cntr=0.3,0.1

Type RM Length L Ch R = 1 ,8880.4  ,128.8,124.4,123.3
XS GIS Cut Line= 2
     1772000.048      360808.118     1771827.522      361034.897
#Sta/Elev= 30
       0  964.06     7.9  960.83    19.8  958.97    39.6  957.16    55.4  956.22
    63.3  954.51    79.2  955.82    87.1  955.59   102.9  953.66   114.8  951.19
   122.7  950.83   130.6  948.81   134.6  947.46   138.5  947.34   146.4     948
   150.4  949.34   154.4  952.16   158.3  953.62   162.3  954.12   174.1  953.53
     190  953.66   201.8  955.93   217.7  957.79   225.6  959.62   233.5  963.11
   245.4  970.01   249.3   972.4   257.2   978.1   265.2  982.69     285  995.38
#Mann= 3 , 0 , 0
       0      .1       0   130.6    .045       0   150.4     .08       0
Bank Sta=130.6,150.4
XS Rating Curve= 0 ,0
Exp/Cntr=0.3,0.1

Type RM Length L Ch R = 1 ,8756    ,245.3,250.3,252.4
XS GIS Cut Line= 2
     1771893.711      360738.674      1771730.95      360964.368
#Sta/Elev= 30
       0  964.15       8  960.11    15.9  957.19    35.8  955.61    91.4  954.71
    95.4  954.15   103.4  951.84   115.1  946.92   119.2  945.37   127.2  944.67
   131.2  945.24   135.2  947.65   139.1  950.62   143.1  951.92   151.1  952.15
   174.9  951.71   178.9  952.02   190.8  954.45   194.8  955.83   202.7   960.4
   206.7  961.71   214.7  962.74   218.6  963.65   222.6   965.3   226.6  967.28
   234.5  972.45   238.5   974.6   254.4  982.56   262.4  985.83   278.3  994.03
#Mann= 3 , 0 , 0
       0      .1       0   115.1    .045       0   135.2      .1       0
#XS Ineff= 2 , 0
                          154.38          959.36
Permanent Ineff=
       F       F
Bank Sta=115.1,135.2
XS Rating Curve= 0 ,0
Exp/Cntr=0.3,0.1

Type RM Length L Ch R = 1 ,8505.7  ,251.5,244.2,238.7
XS GIS Cut Line= 3
     1771689.718      360622.571      1771653.91      360650.783
     1771549.744      360778.821
#Sta/Elev= 30
       0  965.18     3.8   961.6     7.6  958.62    11.4  956.81    15.2  955.84
      19  955.12    26.6  953.98    45.6  951.97    49.5  950.58    57.4  944.16
    61.3  942.74    69.2  942.21      77  942.35      81  943.15    92.8  945.27
    96.7  946.36   104.5  949.13   108.5  949.92   112.4  950.43     132  950.26
   147.8  949.35   151.7  949.46   155.6  950.39   159.6  952.06   171.4  958.95
   179.2   962.9   194.9     970   202.8  973.08   206.7  975.76   210.6  979.26
#Mann= 3 , 0 , 0
       0      .1       0    61.3    .045       0      81      .1       0
Bank Sta=61.3,81
XS Rating Curve= 0 ,0
Exp/Cntr=0.3,0.1

Type RM Length L Ch R = 1 ,8261.6  ,259.6,259.2,258.5
XS GIS Cut Line= 3
      1771484.64      360475.002     1771446.662      360519.489
     1771340.325      360693.101
#Sta/Elev= 30
       0  965.29    15.6  959.78    23.4  957.62    35.1  953.66    46.8   951.1
    54.6  950.01    58.5  949.08    70.5  944.58    93.4  939.08   102.4  937.33
   106.4  937.18   110.4  938.44   114.4  940.69   118.4  943.36   122.4  944.96
   126.4  945.81   130.4  946.04   150.3  945.14   158.3  944.32   162.3   944.8
   166.3  946.18   170.3  948.21   182.2  956.69   186.2  959.03   202.2  966.61
   218.2  974.66   222.2  976.35   226.2  977.51   238.1  983.67   262.1   994.7
#Mann= 3 , 0 , 0
       0      .1       0    93.4    .045       0   114.4      .1       0
Bank Sta=93.4,114.4
XS Rating Curve= 0 ,0
Exp/Cntr=0.3,0.1

Type RM Length L Ch R = 1 ,8002.3  ,211.7,194.4,176.7
XS GIS Cut Line= 4
     1771240.499      360362.154     1771214.457      360404.472
     1771153.693      360507.554     1771123.311      360576.998
#Sta/Elev= 30
       0  942.39    26.8  942.09    34.4  941.67    45.9  940.61    57.7  938.95
    61.6  937.66    65.6  935.51    69.6     934    73.6  933.54    85.6  933.04
    93.6  934.04   109.5  937.39   117.5  938.61   137.4  938.48   153.4   937.4
   161.4  938.05   165.4  938.88   169.4  940.55   173.3  942.94   177.3  945.92
   181.3  949.36   189.3  959.28   193.3  963.74   197.3  967.92   201.3  971.65
   213.2  980.52   221.2  986.06   229.2  992.95   241.2 1002.63   245.2 1006.14
#Mann= 3 , 0 , 0
       0      .1       0    69.6    .045       0    93.6     .08       0
Bank Sta=69.6,93.6
XS Rating Curve= 0 ,0
Exp/Cntr=0.3,0.1

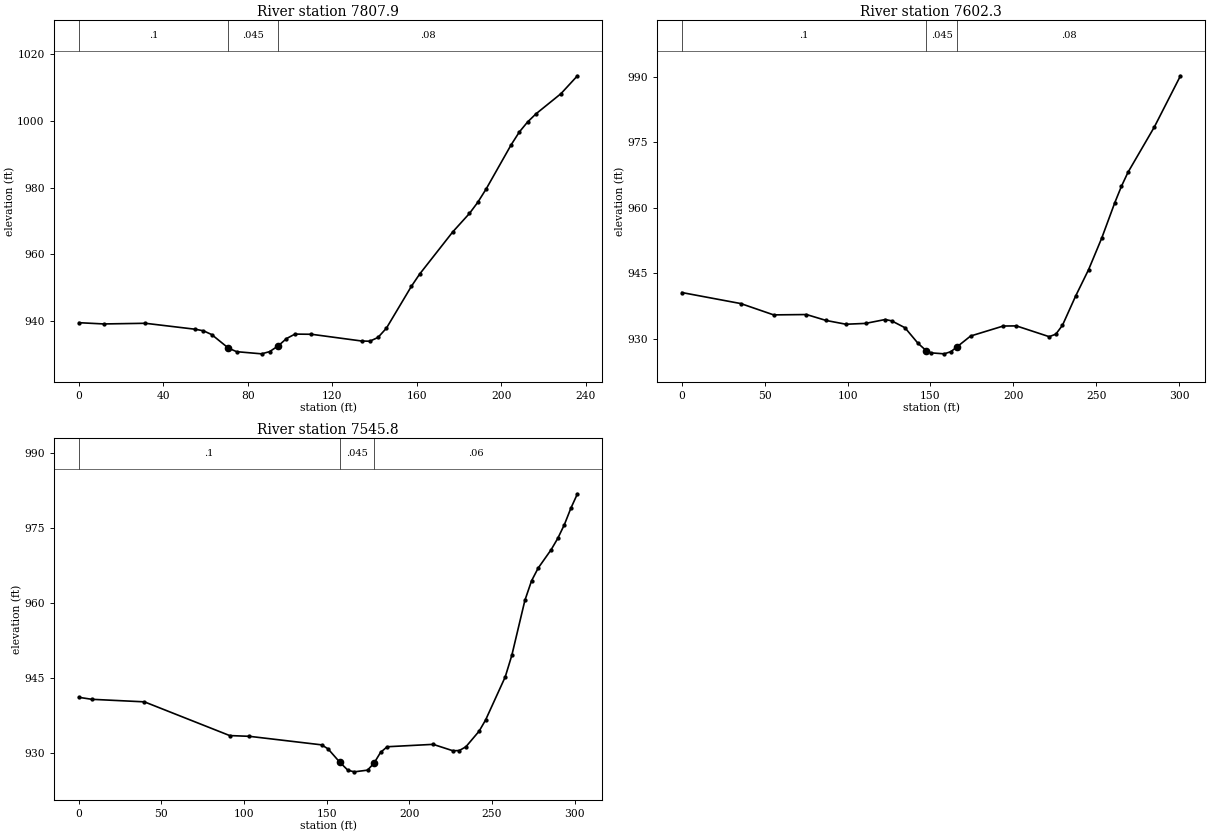
Type RM Length L Ch R = 1 ,7807.9  ,213,205.6,198.3
XS GIS Cut Line= 2
     1771016.975      360303.561     1771000.699      360539.021
#Sta/Elev= 30
       0   939.4    11.8  939.02    31.5  939.22    55.1  937.43      59  936.96
    62.9  935.83    70.8  931.77    74.7  930.69    86.5  930.04    90.3   930.7
    94.4  932.44    98.3  934.63   102.3  935.97   110.1  935.92   133.8   933.9
   137.7  933.83   141.6  934.96   145.6  937.76   157.4  950.32   161.3  953.99
     177  966.69   184.9  972.23   188.8  975.54   192.8  979.58   204.6  992.82
   208.5   996.7   212.4   999.7   216.4 1002.16   228.2 1008.21     236 1013.58
#Mann= 3 , 0 , 0
       0      .1       0    70.8    .045       0    94.4     .08       0
Bank Sta=70.8,94.4
XS Rating Curve= 0 ,0
Exp/Cntr=0.3,0.1

Type RM Length L Ch R = 1 ,7602.3  ,57.2,56.5,55.8
XS GIS Cut Line= 2
      1770786.94      360221.095     1770824.917      360519.489
#Sta/Elev= 30
       0  940.56    35.6  938.03    55.4  935.44    75.2  935.52    87.1  934.16
      99   933.3   110.8  933.49   122.7  934.38   126.6  934.07   134.6   932.5
   142.5  928.92   147.4  927.26   150.4  926.74   158.3  926.52   162.3  927.02
   166.2  928.18   174.2   930.6   193.9  932.89   201.8  932.92   221.6  930.45
   225.6  931.03   229.6  933.05   237.5  939.71   245.4  945.83   253.3  953.03
   261.2  961.16   265.2   964.9   269.1  968.07     285  978.45   300.8   990.2
#Mann= 3 , 0 , 0
       0      .1       0   147.4    .045       0   166.2     .08       0
Bank Sta=147.4,166.2
XS Rating Curve= 0 ,0
Exp/Cntr=0.3,0.1

Type RM Length L Ch R = 1 ,7545.8  ,43.3,43.2,43.3
XS GIS Cut Line= 2
     1770727.261      360224.351     1770771.749      360522.745
#Sta/Elev= 30
       0  941.12     7.9  940.72    39.7  940.21    91.3  933.45   103.2   933.3
   146.9  931.59   150.8  930.79   157.8  928.15   162.8   926.5   166.7  926.18
   174.7  926.52   178.6  927.91   182.6  930.09   186.6  931.21   214.4  931.69
   226.3  930.41   230.2  930.45   234.2   931.2   242.2  934.33   246.1  936.56
     258  945.21     262  949.55   269.9  960.56   273.9  964.45   277.9  967.01
   285.8  970.72   289.8  972.99   293.8  975.74   297.7  979.02   301.7  981.92
#Mann= 3 , 0 , 0
       0      .1       0   157.8    .045       0   178.6     .06       0
Bank Sta=157.8,178.6
XS Rating Curve= 0 ,0
Exp/Cntr=0.3,0.1