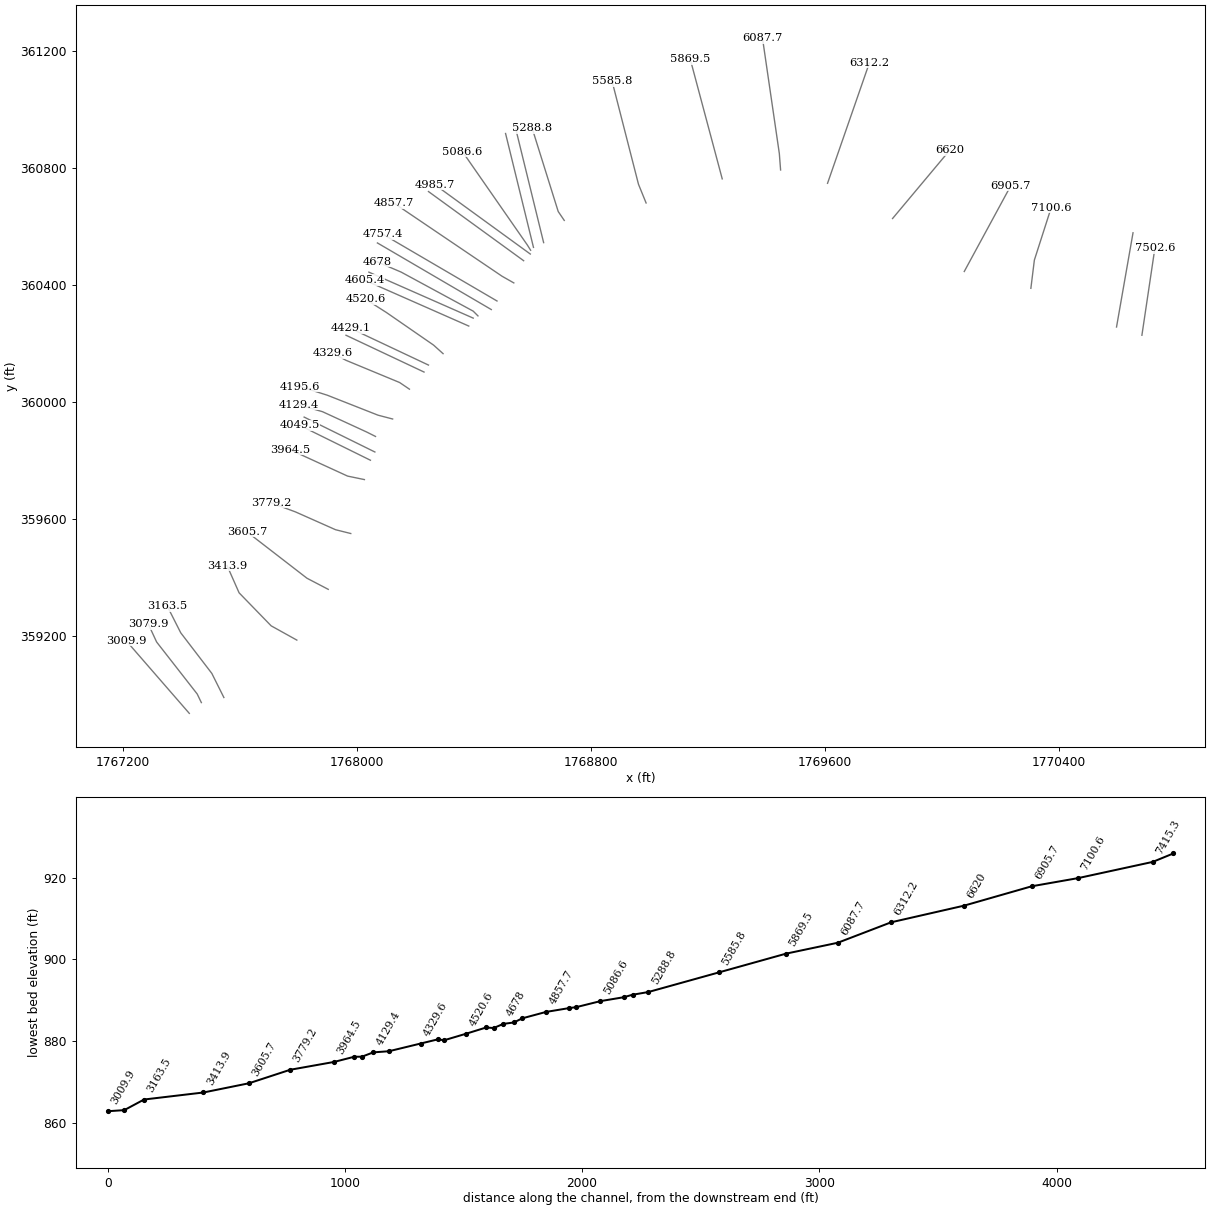
HEC-RAS study WHITESBR.prj: WHITESBR

--- WHITESBR.g01 (geometry) --- (continued)

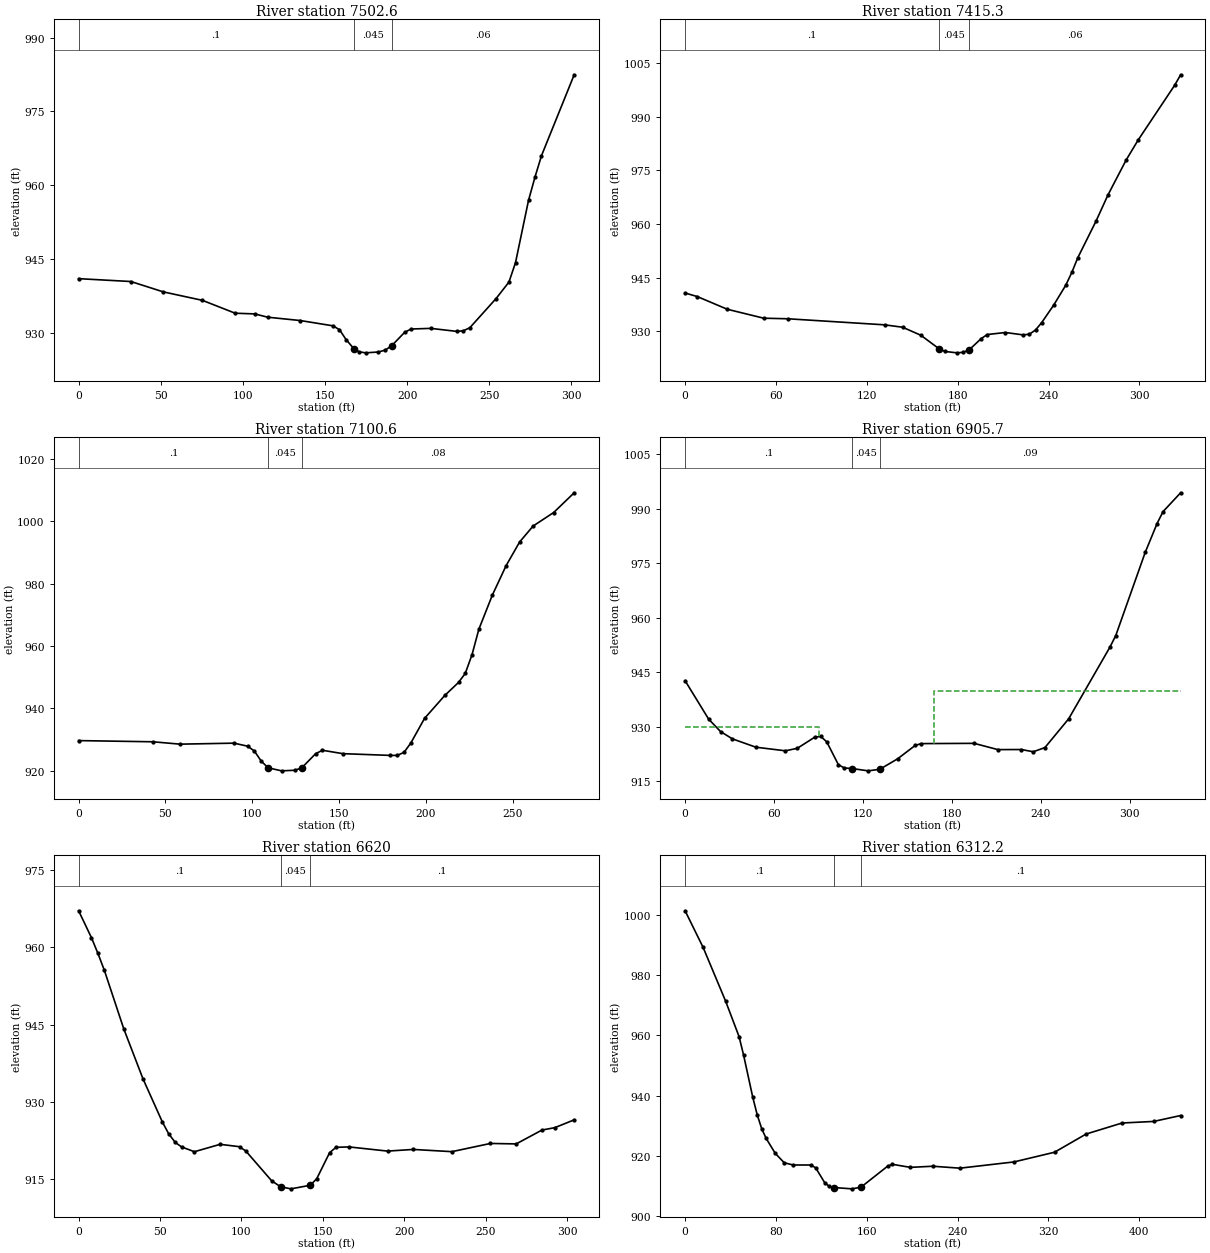
Type RM Length L Ch R = 1 ,7502.6  ,88.2,87.3,86.2
XS GIS Cut Line= 2
     1770684.943      360228.691     1770729.431      360527.085
#Sta/Elev= 30
       0  941.04    31.8  940.46    51.6  938.35    75.4  936.63    95.3  934.02
   107.2  933.88   115.1  933.21     135  932.53   154.8  931.46   158.8  930.68
   162.8  928.68   167.5  926.84   170.7  926.19   174.7  925.97   182.5  926.14
   186.6  926.52   190.5  927.38   198.5  930.14   202.4  930.81   214.4  930.94
   230.2  930.33   234.2  930.45   238.2  931.08   254.1  936.98     262  940.35
     266  944.32   273.9  956.94   277.9  961.74   281.8  966.02   301.7  982.46
#Mann= 3 , 0 , 0
       0      .1       0   167.5    .045       0   190.5     .06       0
Bank Sta=167.5,190.5
XS Rating Curve= 0 ,0
Exp/Cntr=0.3,0.1

Type RM Length L Ch R = 1 ,7415.3  ,316.7,314.7,309.4
XS GIS Cut Line= 2
     1770598.138      360256.903     1770654.561      360579.168
#Sta/Elev= 30
       0  940.66       8  939.67    27.9   936.1    51.9   933.6    67.8  933.44
   131.7  931.74   143.6  931.07   155.6  928.83   167.6  925.06   171.6  924.28
   179.5  923.89   183.5  924.03   187.5   924.7   195.5  927.88   199.5  929.02
   211.5  929.59   223.4  928.91   227.4  929.14   231.4   930.3   235.4  932.33
   243.4  937.28   251.4  942.88   255.4  946.48   259.3  950.56   271.3  960.78
   279.3  968.22   291.3     978   299.2  983.58   323.2  998.86   327.2 1001.83
#Mann= 3 , 0 , 0
       0      .1       0   167.6    .045       0   187.5     .06       0
Bank Sta=167.6,187.5
XS Rating Curve= 0 ,0
Exp/Cntr=0.3,0.1

Type RM Length L Ch R = 1 ,7100.6  ,205.1,194.9,187.9
XS GIS Cut Line= 3
     1770305.169      360389.281     1770317.105      360485.852
     1770374.614      360664.889
#Sta/Elev= 30
       0  929.62    42.8  929.24    58.4  928.48    89.5   928.8    97.3  927.83
   101.2  926.28   105.1  923.09   109.1  920.89   116.9  919.92   124.7  920.11
   128.6  920.94   136.5  925.42   140.4  926.52   152.2  925.43   179.6  924.87
   183.5  924.87   187.4  925.85   191.3  928.82   199.2  936.73   210.9  944.11
   218.8  948.28   222.7   951.2   226.6  957.24   230.5  965.34   238.3  976.33
   246.2  985.74     254  993.35   261.8  998.47   273.6 1002.79   285.4 1009.12
#Mann= 3 , 0 , 0
       0      .1       0   109.1    .045       0   128.6     .08       0
Bank Sta=109.1,128.6
XS Rating Curve= 0 ,0
Exp/Cntr=0.3,0.1

Type RM Length L Ch R = 1 ,6905.7  ,292.7,285.7,278.3
XS GIS Cut Line= 2
     1770077.304       360446.79      1770236.81      360740.844
#Sta/Elev= 30
       0  942.72    15.9  932.15    23.9  928.75    31.9  926.73    47.8  924.43
    67.7  923.44    75.7  924.12    87.6  927.21    91.6  927.38    95.6  925.92
   103.5   919.6   107.5  918.72   112.8  918.56   123.5  917.93   131.4  918.35
   143.4  921.22   155.3  924.91   159.3  925.42   195.1  925.49   211.1  923.77
     227  923.79     235  923.18   242.9  924.33   258.9  932.23   286.7   951.9
   290.7  955.13   310.6  978.03   318.6  985.96   322.6  989.22   334.5  994.41
#Mann= 3 , 0 , 0
       0      .1       0   112.8    .045       0   131.4     .09       0
#XS Ineff= 2 , 0
           90.52   930.1  167.71           939.8
Permanent Ineff=
       F       F
Bank Sta=112.8,131.4
XS Rating Curve= 0 ,0
Exp/Cntr=0.3,0.1

Type RM Length L Ch R = 1 ,6620    ,294,307.8,321.2
XS GIS Cut Line= 2
     1769832.079      360627.996     1770027.391      360861.286
#Sta/Elev= 30
       0  967.03     7.9   961.8    11.8  958.81    15.8   955.5    27.7  944.18
    39.5   934.5    51.4  926.14    55.3  923.84    59.3  922.18    63.2   921.3
    71.1  920.37    86.9   921.8    98.8  921.34   102.7  920.49   118.5  914.75
     124  913.58   130.4  913.18   142.2  913.87   146.2  915.13   154.1  920.17
     158  921.22     166   921.3   189.7  920.49   205.5  920.81   229.2  920.38
   252.9  921.97   268.7  921.88   284.5  924.56   292.4  925.03   304.3  926.54
#Mann= 3 , 0 , 0
       0      .1       0     124    .045       0   142.2      .1       0
Bank Sta=124,142.2
XS Rating Curve= 0 ,0
Exp/Cntr=0.3,0.1

Type RM Length L Ch R = 1 ,6312.2  ,205.7,224.4,241.8
XS GIS Cut Line= 2
      1769609.64      360748.439     1769752.869      361160.766
#Sta/Elev= 30
       0 1001.26    15.9   989.1    35.7   971.3    47.6  959.49    51.6   953.3
    59.5  939.63    63.5  933.65    67.5     929    71.4  925.82    79.4  920.87
    87.3  917.75    95.2     917   111.1     917   115.1  916.01     123  911.12
     127  909.91     131  909.54   146.8   909.1   154.8  909.61   178.6  916.67
   182.5  917.23   198.4  916.22   218.2  916.59   242.1  915.95   289.7  918.02
   325.4  921.23   353.2  927.26   384.9  930.92   412.7  931.44   436.5   933.4
#Mann= 3 , 0 , 0
       0      .1       0     131    .045       0   154.8      .1       0
Bank Sta=131,154.8
XS Rating Curve= 0 ,0
Exp/Cntr=0.3,0.1

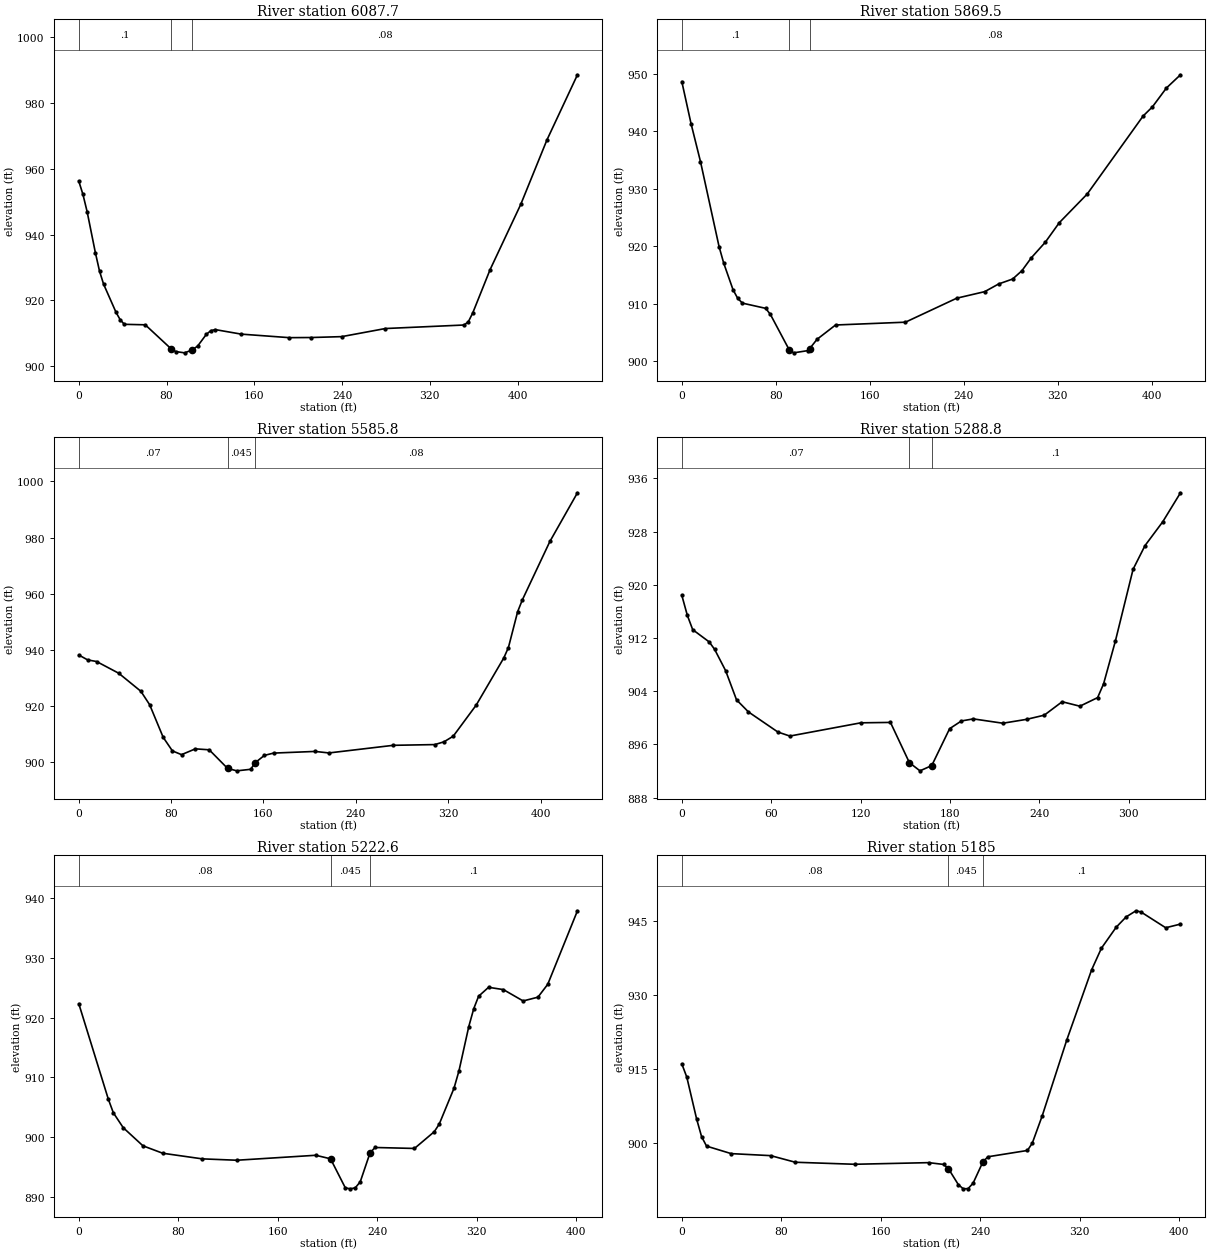
Type RM Length L Ch R = 1 ,6087.7  ,213.5,218.2,222.4
XS GIS Cut Line= 3
     1769449.049      360794.012     1769444.709      360850.436
       1769387.2      361244.316
#Sta/Elev= 30
       0  956.22     3.8  952.18     7.6  946.96    15.1  934.54    18.9  928.91
    22.6  924.96      34  916.36    37.7  914.18    41.5  912.76    60.6  912.61
    84.4  905.25    88.4  904.49    96.4   904.1   102.8   904.9   108.3  906.13
   116.3  909.72   120.3  910.81   124.3  911.16   148.1  909.78   191.9  908.71
   211.8  908.75   239.7  909.02   279.5  911.48   351.2  912.55   355.1  913.52
   359.1  916.18     375  929.39   402.9  949.16   426.8  968.75   454.6  988.52
#Mann= 3 , 0 , 0
       0      .1       0    84.4    .045       0   102.8     .08       0
Bank Sta=84.4,102.8
XS Rating Curve= 0 ,0
Exp/Cntr=0.3,0.1

Type RM Length L Ch R = 1 ,5869.5  ,283.8,283.7,282.9
XS GIS Cut Line= 2
     1769249.397       360763.63     1769139.804      361173.786
#Sta/Elev= 30
       0  948.68     7.9  941.32    15.9  934.74    31.7  919.95    35.7  917.04
    43.6  912.43    47.6  910.92    51.6  910.09    71.4  909.18    75.4  908.13
    91.3  902.01    95.2  901.43   107.1  901.81   108.9  902.17   115.1  903.78
   130.9  906.28   190.4  906.77   234.1  910.95   257.9  912.09   269.8  913.43
   281.7  914.29   289.6  915.74   297.6  917.99   309.5   920.7   321.4   924.1
   345.2   929.1   392.8  942.69   400.7  944.28   412.6  947.56   424.6  949.87
#Mann= 3 , 0 , 0
       0      .1       0    91.3    .045       0   108.9     .08       0
Bank Sta=91.3,108.9
XS Rating Curve= 0 ,0
Exp/Cntr=0.3,0.1

Type RM Length L Ch R = 1 ,5585.8  ,294.8,297.1,298.8
XS GIS Cut Line= 3
      1768988.98      360681.165     1768962.938      360745.184
     1768872.877      361096.746
#Sta/Elev= 30
       0  938.13     7.7  936.38    15.4  935.81    34.6  931.63    53.8  925.19
    61.4   920.4    73.1  908.79    81.1  903.94      89   902.6     101  904.67
     113  904.33   128.9   897.7   136.9  896.83   148.9  897.38   152.9  899.76
   160.8  902.34   168.8  903.16   204.7  903.75   216.7  903.21   272.5  905.93
   308.4  906.19   316.4  907.18   324.4  909.19   344.3  920.28   368.2  937.09
   372.2   940.8   380.2  953.59   384.2  957.73   408.1   978.6     432  995.97
#Mann= 3 , 0 , 0
       0     .07       0   128.9    .045       0   152.9     .08       0
Bank Sta=128.9,152.9
XS Rating Curve= 0 ,0
Exp/Cntr=0.3,0.1

Type RM Length L Ch R = 1 ,5288.8  ,68.8,66.1,64
XS GIS Cut Line= 3
     1768709.032      360621.486     1768688.416      360651.868
      1768599.44      360936.156
#Sta/Elev= 30
       0  918.42     3.7  915.41     7.3  913.26    18.4  911.41      22   910.3
    29.4  907.09    36.7  902.71    44.7  900.89    64.5  897.86    72.5  897.26
   120.1  899.25     140  899.31   152.7  893.26   159.8  892.03   167.7  892.82
   179.7  898.37   187.6  899.53   195.6  899.84   215.4  899.19   231.3  899.77
   243.2   900.4   255.2  902.42   267.1  901.75     279  903.04     283  905.11
   290.9  911.53   302.8  922.34   310.8   925.9   322.7  929.48   334.6  933.84
#Mann= 3 , 0 , 0
       0     .07       0   152.7    .045       0   167.7      .1       0
Bank Sta=152.7,167.7
XS Rating Curve= 0 ,0
Exp/Cntr=0.3,0.1

Type RM Length L Ch R = 1 ,5222.6  ,37.6,37.6,37.6
XS GIS Cut Line= 2
     1768638.502      360545.531     1768543.016      360935.071
#Sta/Elev= 30
       0  922.31    23.8  906.33    27.8  904.08    35.7   901.6    51.6  898.56
    67.5  897.32    99.3  896.38   127.1  896.15   190.6  896.98   202.5  896.39
   214.4  891.53   218.4  891.37   222.4  891.54   226.4  892.55   234.3   897.4
   238.3  898.28     270  898.12   285.9  900.91   289.9  902.18   301.8  908.18
   305.8  911.09   313.7   918.5   317.7  921.49   321.6  923.56   329.6  925.05
   341.5  924.67   357.4  922.77   369.3   923.4   377.2  925.55   401.1  937.84
#Mann= 3 , 0 , 0
       0     .08       0   202.5    .045       0   234.3      .1       0
Bank Sta=202.5,234.3
XS Rating Curve= 0 ,0
Exp/Cntr=0.3,0.1

Type RM Length L Ch R = 1 ,5185    ,84.4,98.4,112.4
XS GIS Cut Line= 2
      1768603.78      360529.255     1768508.294      360918.795
#Sta/Elev= 30
       0   916.1       4  913.41    11.9  904.93    15.9  901.34    19.9  899.42
    39.7   897.9    71.5  897.49    91.3  896.15     139  895.74   198.6  896.07
   210.5  895.71   214.4  894.87   222.4  891.62   226.4  890.76   230.3  890.81
   234.3  891.91   242.2  896.23   246.2  897.26     278  898.54   281.9  900.02
   289.9  905.57   309.7  920.98   329.6  935.14   337.5  939.54   349.4   943.8
   357.4  945.89   365.3  947.13   369.3  946.89   389.2  943.69   401.1  944.43
#Mann= 3 , 0 , 0
       0     .08       0   214.4    .045       0   242.2      .1       0
Bank Sta=214.4,242.2
XS Rating Curve= 0 ,0
Exp/Cntr=0.3,0.1

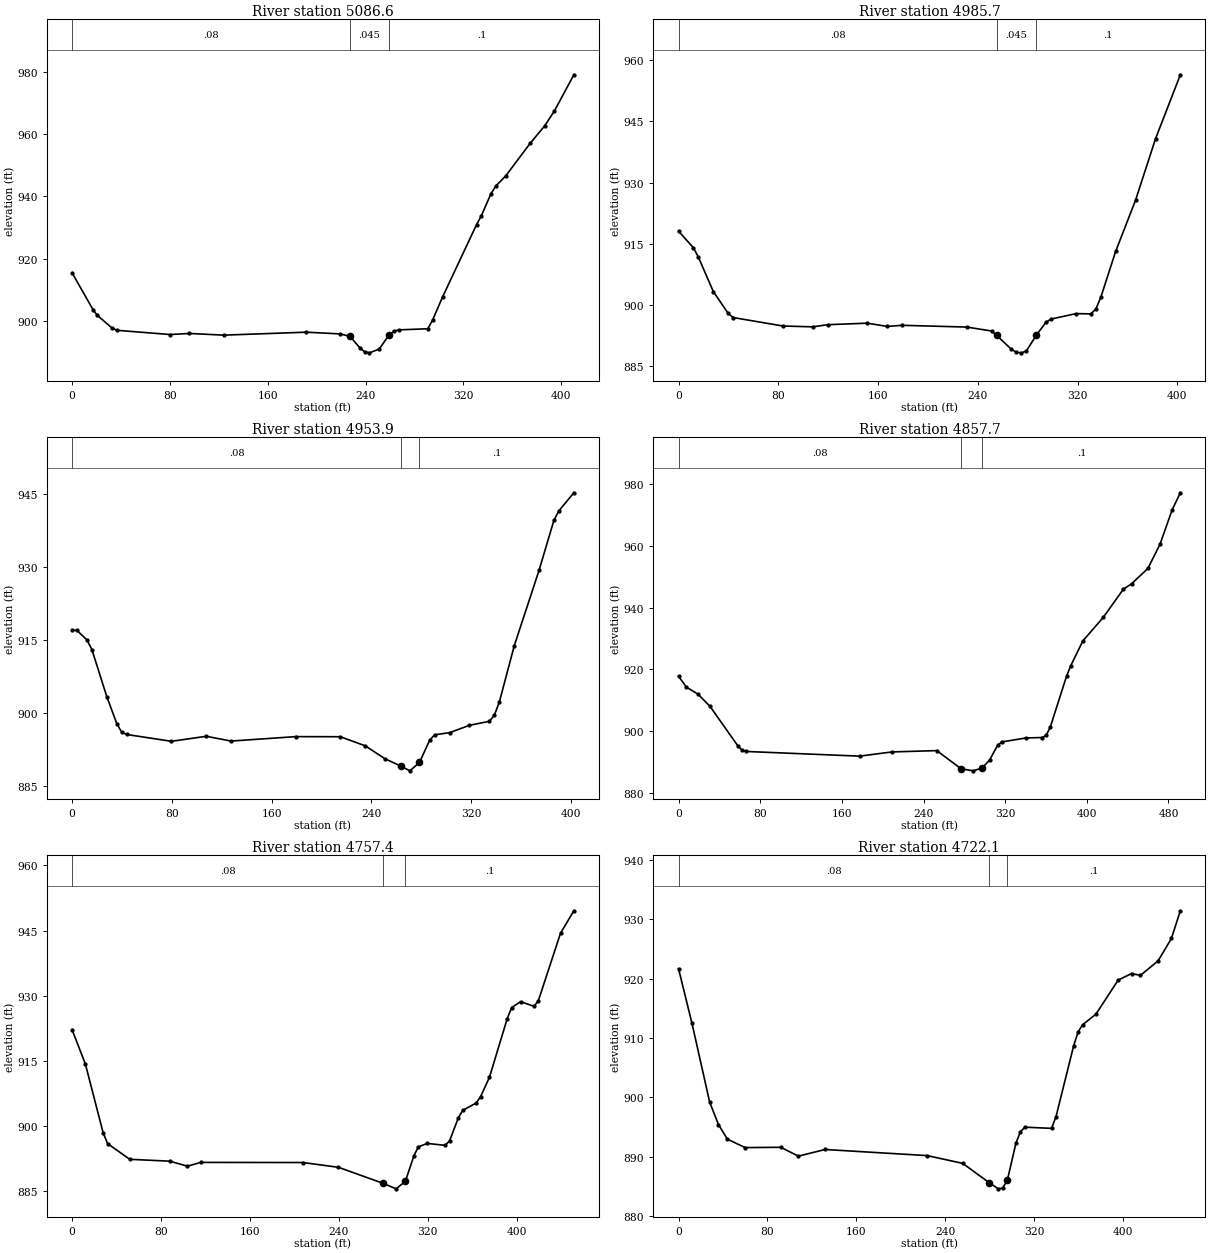
Type RM Length L Ch R = 1 ,5086.6  ,88.1,100.9,113.4
XS GIS Cut Line= 3
     1768594.015      360519.489     1768583.164      360536.851
     1768360.725      360856.946
#Sta/Elev= 30
       0  915.48    17.1  903.68    20.5  901.88    32.4  897.85    36.4  897.04
    80.1  895.68      96  896.02   123.9  895.48   191.5  896.43   219.4  895.87
   227.3  895.06   235.2  891.46   239.2  890.14   243.2   889.8   251.2  891.02
   259.1  895.53   263.1   896.7   267.1  897.17   290.9  897.53   294.9  900.42
   302.9  907.69   330.7  930.93   334.7  933.84   342.6  940.94   346.6  943.39
   354.6   946.6   374.5  957.02   386.4  962.63   394.4  967.44   410.3  979.05
#Mann= 3 , 0 , 0
       0     .08       0   227.3    .045       0   259.1      .1       0
Bank Sta=227.3,259.1
XS Rating Curve= 0 ,0
Exp/Cntr=0.3,0.1

Type RM Length L Ch R = 1 ,4985.7  ,32.2,31.9,31.8
XS GIS Cut Line= 2
     1768592.929      360506.469     1768267.409      360743.014
#Sta/Elev= 30
       0  918.14      12  914.02    15.9  911.78    27.9  903.34    39.8     898
    43.8  896.98    83.7  894.91   107.6   894.7   119.5  895.23   151.4   895.6
   167.3  894.81   179.3  895.08   231.1  894.65     251  893.69     255  892.65
   266.9  889.22   270.9  888.47   274.9  888.34   278.9  888.77   286.8  892.61
   294.8  895.87   298.8  896.61   318.7  897.94   330.7  897.88   334.7  899.08
   338.6  901.91   350.6  913.23   366.5  925.72   382.5  940.74   402.4  956.41
#Mann= 3 , 0 , 0
       0     .08       0     255    .045       0   286.8      .1       0
Bank Sta=255,286.8
XS Rating Curve= 0 ,0
Exp/Cntr=0.3,0.1

Type RM Length L Ch R = 1 ,4953.9  ,94.4,96.2,97.1
XS GIS Cut Line= 2
     1768570.143      360483.682     1768244.622      360720.227
#Sta/Elev= 30
       0  917.01       4  916.93      12  914.96    15.9  913.01    27.9  903.29
    35.9  897.77    39.8  896.03    43.8  895.56    79.7  894.16   107.6  895.19
   127.5  894.21   179.3  895.12   215.1   895.1   235.1  893.23     251  890.56
   263.6  889.07   270.9  888.09   278.6  889.82   286.8   894.4   290.8   895.5
   302.8  895.94   318.7  897.45   334.7  898.27   338.6   899.5   342.6  902.19
   354.6  913.79   374.5   929.3   386.4  939.57   390.4  941.53   402.4  945.23
#Mann= 3 , 0 , 0
       0     .08       0   263.6    .045       0   278.6      .1       0
Bank Sta=263.6,278.6
XS Rating Curve= 0 ,0
Exp/Cntr=0.3,0.1

Type RM Length L Ch R = 1 ,4857.7  ,98,100.3,102.8
XS GIS Cut Line= 3
     1768536.506      360407.727     1768496.358      360430.514
     1768127.435       360680.08
#Sta/Elev= 30
       0  917.81     7.7  914.28    19.2  911.97    30.8  908.05    58.1  895.27
    62.1  893.88      66  893.44   177.4  891.92   209.2  893.29     253  893.71
   276.8  887.83   288.8  887.16   297.6  888.11   304.7  890.64   312.6  895.44
   316.6  896.52   340.4  897.81   356.4  897.96   360.3  898.73   364.3  901.44
   380.2  917.89   384.2  921.18   396.1  929.25     416  936.84   435.9  946.04
   443.8  947.74   459.8  952.72   471.7  960.57   483.6  971.72   491.6  977.24
#Mann= 3 , 0 , 0
       0     .08       0   276.8    .045       0   297.6      .1       0
Bank Sta=276.8,297.6
XS Rating Curve= 0 ,0
Exp/Cntr=0.3,0.1

Type RM Length L Ch R = 1 ,4757.4  ,35.3,35.3,35.3
XS GIS Cut Line= 2
     1768478.997      360345.878     1768089.457      360573.743
#Sta/Elev= 30
       0  922.19      12  914.27      28  898.42      32  895.98    51.9  892.38
    87.9  891.95   103.8   890.8   115.8  891.67   207.7  891.64   239.6  890.54
   279.6  886.87   291.5  885.59   299.8  887.34   307.5  893.23   311.5  895.26
   319.5  896.03   335.5   895.6   339.5  896.61   347.4  901.92   351.4  903.65
   363.4  905.32   367.4  906.78   375.4  911.26   391.4  924.76   395.4  927.28
   403.4  928.64   415.4  927.57   419.3  928.81   439.3  944.38   451.3  949.54
#Mann= 3 , 0 , 0
       0     .08       0   279.6    .045       0   299.8      .1       0
Bank Sta=279.6,299.8
XS Rating Curve= 0 ,0
Exp/Cntr=0.3,0.1

Type RM Length L Ch R = 1 ,4722.1  ,42.9,44.2,45.1
XS GIS Cut Line= 2
     1768459.466      360316.582     1768069.926      360544.446
#Sta/Elev= 30
       0  921.67      12  912.54      28  899.18    35.9  895.42    43.9  892.96
    59.9  891.53    91.9  891.58   107.8  890.09   131.8  891.21   223.6  890.18
   255.6  888.87   279.6  885.59   287.6  884.58   291.5   884.7   295.7  886.02
   303.5  892.32   307.5   894.2   311.5  894.97   335.5  894.77   339.5  896.76
   355.4   908.7   359.4  911.04   363.4  912.22   375.4  914.02   395.4  919.75
   407.4  920.86   415.4  920.54   431.3  922.99   443.3  926.77   451.3  931.43
#Mann= 3 , 0 , 0
       0     .08       0   279.6    .045       0   295.7      .1       0
Bank Sta=279.6,295.7
XS Rating Curve= 0 ,0
Exp/Cntr=0.3,0.1

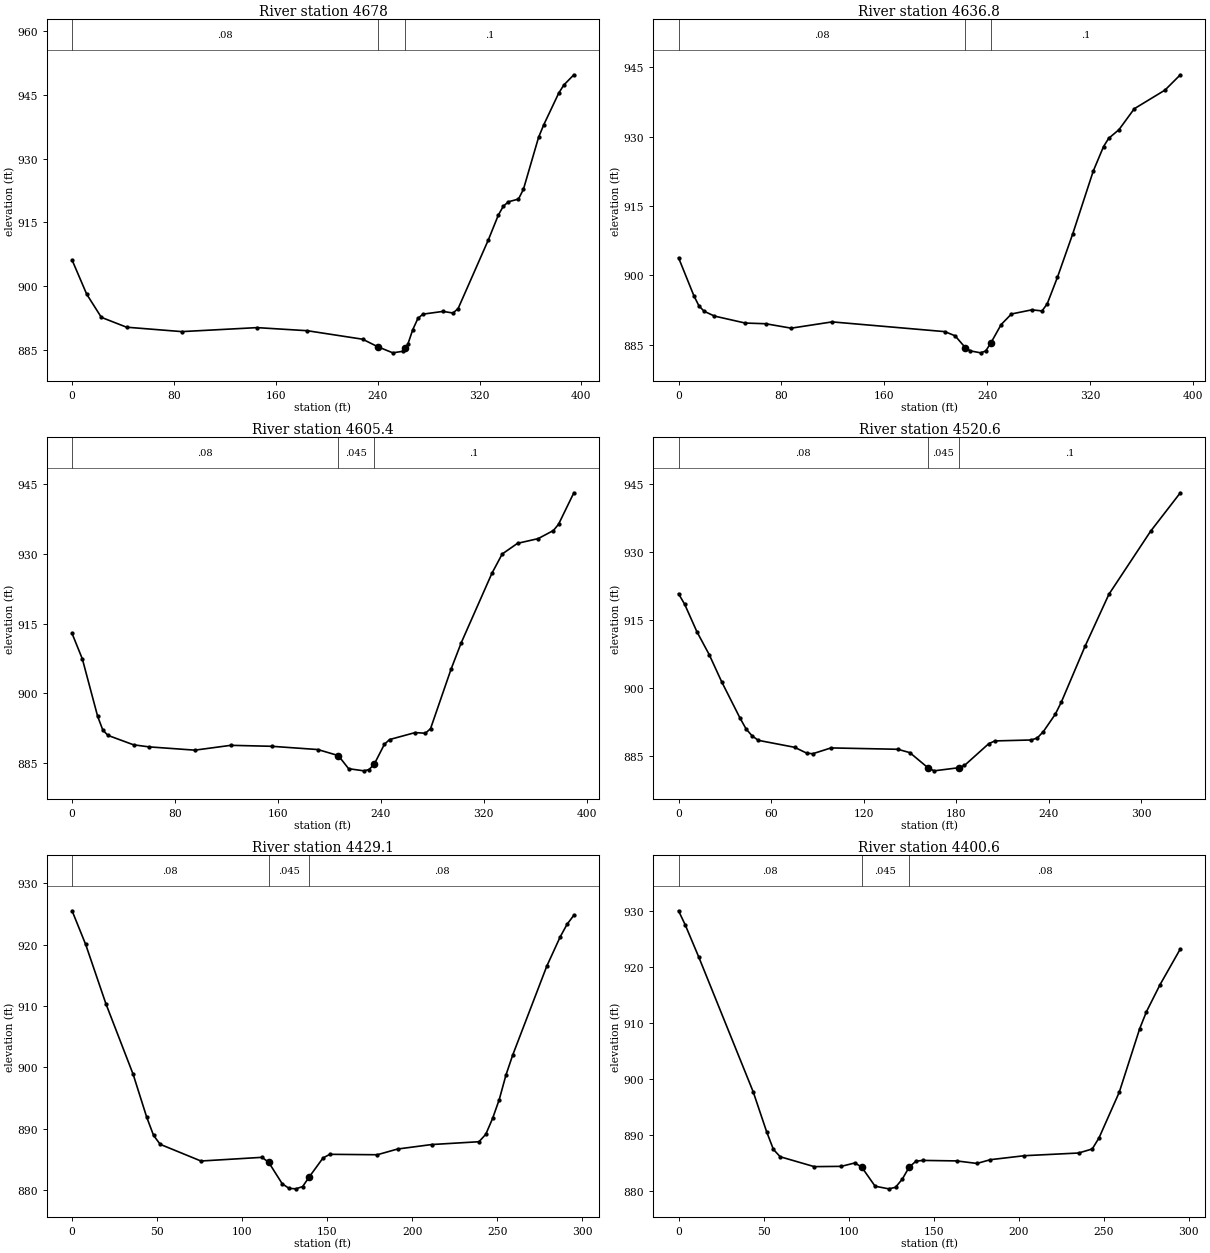
Type RM Length L Ch R = 1 ,4678    ,37.9,41.2,44.3
XS GIS Cut Line= 4
     1768413.893       360294.88     1768397.617      360311.156
     1768151.306       360444.62     1768067.756      360480.427
#Sta/Elev= 30
       0   906.1    11.5  898.04      23  892.59    42.8  890.27    86.2  889.23
   145.3  890.17   184.8  889.44   228.2  887.44     240  885.68   251.9  884.23
   259.8   884.6   261.5  885.32   263.7  886.25   267.6   889.7   271.6  892.33
   275.5  893.34   291.3  893.99   299.2  893.61   303.2  894.66   326.9  910.81
   334.8  916.69   338.7  918.77   342.7  919.81   350.6  920.45   354.5  922.76
   366.4  935.01   370.4  937.91   382.2   945.4   386.2  947.31   394.1  949.73
#Mann= 3 , 0 , 0
       0     .08       0     240    .045       0   261.5      .1       0
Bank Sta=240,261.5
XS Rating Curve= 0 ,0
Exp/Cntr=0.3,0.1

Type RM Length L Ch R = 1 ,4636.8  ,31.3,31.4,31.3
XS GIS Cut Line= 2
     1768397.617      360287.285     1768040.629       360444.62
#Sta/Elev= 30
       0  903.81    11.9   895.6    15.9  893.37    19.9  892.22    27.9  891.18
    51.8  889.67    67.7  889.52    87.6  888.56   119.4  889.92     207  887.81
     215  886.91   222.9  884.36   226.9  883.64   234.9  883.22   238.8  883.62
   242.8  885.36   250.8  889.34   258.8  891.63   274.7  892.53   282.6  892.29
   286.6  893.82   294.6   899.6   306.5  909.01   322.4  922.56   330.4  927.87
   334.4  929.65   342.4  931.53   354.3  936.06   378.2   940.1   390.1  943.41
#Mann= 3 , 0 , 0
       0     .08       0   222.9    .045       0   242.8      .1       0
Bank Sta=222.9,242.8
XS Rating Curve= 0 ,0
Exp/Cntr=0.3,0.1

Type RM Length L Ch R = 1 ,4605.4  ,92.2,84.8,77
XS GIS Cut Line= 2
     1768382.426      360260.158     1768025.438      360417.493
#Sta/Elev= 30
       0  912.91       8  907.42    19.9  895.06    23.9  892.13    27.9  890.98
    47.8  888.95    59.7  888.51    95.5   887.8   123.4  888.84   155.2  888.63
   191.1  887.93     207  886.63     215  883.81   226.9  883.35   230.9  883.63
   234.9  884.78   242.8  889.05   246.8  890.08   266.7  891.58   274.7  891.44
   278.7  892.44   294.6   905.2   302.5  910.88   326.4  925.86   334.4  930.01
   346.3   932.3   362.3  933.31   374.2  935.06   378.2  936.41   390.1  943.18
#Mann= 3 , 0 , 0
       0     .08       0     207    .045       0   234.9      .1       0
Bank Sta=207,234.9
XS Rating Curve= 0 ,0
Exp/Cntr=0.3,0.1

Type RM Length L Ch R = 1 ,4520.6  ,84.9,91.5,98.2
XS GIS Cut Line= 4
     1768294.535      360165.757     1768261.983      360195.054
     1768100.308      360306.816     1768028.693      360352.389
#Sta/Elev= 30
       0  920.84       4   918.5    11.9  912.47    19.9  907.41    27.9  901.48
    39.8  893.47    43.8  891.04    47.7  889.52    51.7  888.54    75.2  887.01
    83.1  885.71      87  885.59    98.8  886.87   142.1  886.57   149.9  885.83
   161.7  882.48   165.6  881.82   181.5   882.5   185.3     883     201  887.79
     205  888.41   228.6  888.62   232.5  889.06   236.4  890.45   244.2  894.31
   248.1  896.98   263.5   909.3   278.9  920.71   305.9  934.59   325.2  943.08
#Mann= 3 , 0 , 0
       0     .08       0   161.7    .045       0   181.5      .1       0
Bank Sta=161.7,181.5
XS Rating Curve= 0 ,0
Exp/Cntr=0.3,0.1

Type RM Length L Ch R = 1 ,4429.1  ,28.5,28.5,28.5
XS GIS Cut Line= 2
     1768244.622      360126.694     1767977.695      360252.562
#Sta/Elev= 30
       0  925.51       8  920.03    19.9  910.37    35.9   898.9    43.9   891.9
    47.9  888.96    51.8  887.49    75.8  884.77   111.7  885.37   115.6  884.57
   123.6  881.06   127.6  880.32   131.6  880.24   135.6  880.61   139.6  882.23
   147.6  885.27   151.6  885.86   179.5  885.79   191.4  886.72   211.4  887.45
   239.3  887.91   243.3  889.12   247.3   891.7   251.2  894.76   255.2   898.8
   259.2  902.07   279.2  916.51   287.1  921.28   291.1  923.31   295.1  924.78
#Mann= 3 , 0 , 0
       0     .08       0   115.6    .045       0   139.6     .08       0
Bank Sta=115.6,139.6
XS Rating Curve= 0 ,0
Exp/Cntr=0.3,0.1

Type RM Length L Ch R = 1 ,4400.6  ,69.2,71,73
XS GIS Cut Line= 2
     1768229.431      360102.823     1767962.504      360228.691
#Sta/Elev= 30
       0  930.02       4  927.46      12  921.69    43.9  897.74    51.8  890.62
    55.8  887.46    59.8  886.15    79.8  884.39    95.7  884.44   103.7  885.05
   107.7  884.31   115.6   880.9   123.6  880.43   127.6   880.7   131.6  882.17
   135.6  884.28   139.6  885.36   143.6   885.5   163.5  885.41   175.5  884.96
   183.4  885.63   203.4  886.34   235.3  886.82   243.3  887.54   247.3  889.53
   259.2  897.67   271.2  908.99   275.2  912.04   283.2  916.86   295.1  923.22
#Mann= 3 , 0 , 0
       0     .08       0   107.7    .045       0   135.6     .08       0
Bank Sta=107.7,135.6
XS Rating Curve= 0 ,0
Exp/Cntr=0.3,0.1

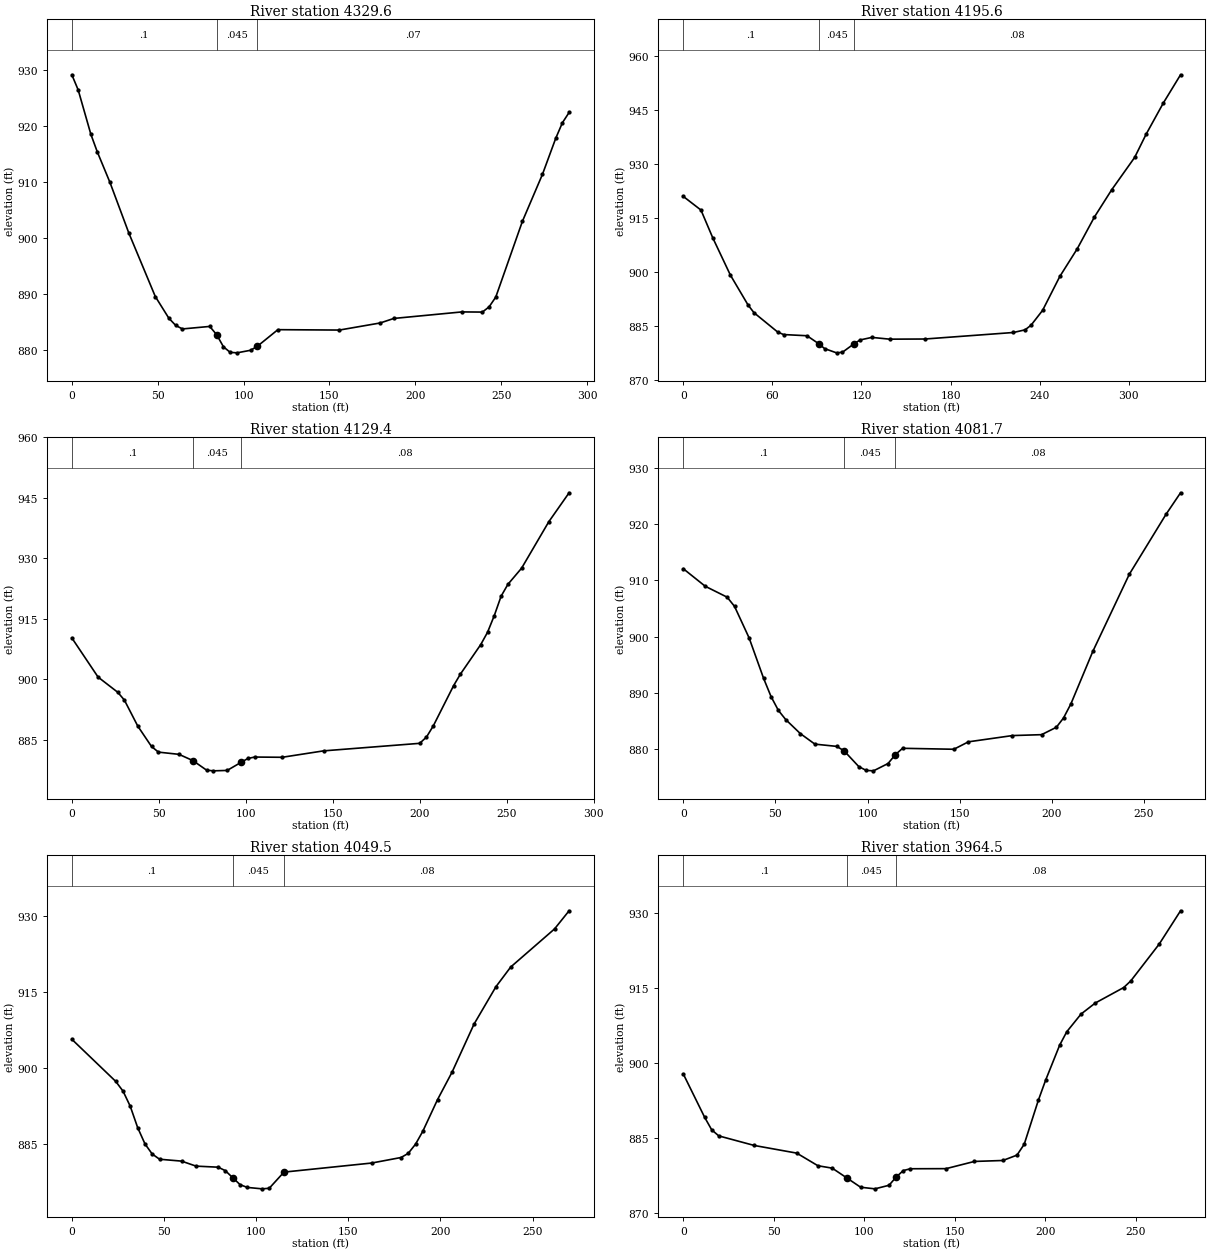
Type RM Length L Ch R = 1 ,4329.6  ,133.1,134,134.5
XS GIS Cut Line= 4
     1768179.518      360044.229     1768145.881      360067.016
     1767962.504       360142.97     1767918.016      360166.842
#Sta/Elev= 30
       0  929.23     3.7  926.51    11.1  918.55    14.8  915.44    22.2  909.95
    33.2  900.88    48.6  889.52    56.5  885.63    60.5  884.34    64.4  883.71
    80.3  884.16    84.3   882.7    88.3  880.51    92.2  879.52    96.2  879.43
   104.1  879.89   108.1  880.62     120  883.58   155.8  883.51   179.6  884.78
   187.5  885.59   227.2  886.76   239.1  886.73     243  887.66   246.9  889.42
   262.4  902.98   274.1  911.41   281.8  917.84   285.7  920.64   289.6  922.48
#Mann= 3 , 0 , 0
       0      .1       0    84.3    .045       0   108.1     .07       0
Bank Sta=84.3,108.1
XS Rating Curve= 0 ,0
Exp/Cntr=0.3,0.1

Type RM Length L Ch R = 1 ,4195.6  ,68.4,66.2,64.1
XS GIS Cut Line= 4
     1768122.009      359942.233     1768072.096      359955.253
     1767898.485      360023.613     1767806.254       360052.91
#Sta/Elev= 30
       0  920.99    11.9   917.2    19.8  909.53    31.7  899.15    43.6  890.84
    47.6  888.69    63.5  883.34    67.5  882.62    83.3  882.29    91.3  880.05
    95.2  878.71   103.2  877.54   107.2  877.71   115.1  880.09   119.1  881.12
     127  881.83   138.9  881.34   162.7  881.38   222.3  883.19   230.2  883.93
   234.2  885.21     242  889.35   253.6  898.77   265.3  906.43   276.9  915.28
   288.5  922.82     304  931.83   311.7  938.26   323.3  946.94   334.9  954.78
#Mann= 3 , 0 , 0
       0      .1       0    91.3    .045       0   115.1     .08       0
Bank Sta=91.3,115.1
XS Rating Curve= 0 ,0
Exp/Cntr=0.3,0.1

Type RM Length L Ch R = 1 ,4129.4  ,48.8,47.7,46.8
XS GIS Cut Line= 4
     1768063.416      359882.554     1768033.034      359897.745
     1767882.209      359967.189     1767799.744      359991.061
#Sta/Elev= 30
       0  910.22    15.1   900.5    26.4  896.74    30.2  894.81    37.9  888.36
    45.8   883.3    49.8   881.9    61.6  881.35    69.6   879.8    77.5  877.42
    81.4  877.26    89.3  877.36    97.2  879.34   101.2  880.32   105.1  880.68
   120.9  880.62   144.7  882.21     200  884.08   203.9  885.64   207.8  888.39
   219.5  898.39   223.4  901.24   235.1  908.57     239  911.61   242.9  915.77
   246.8  920.56   250.7   923.5   258.6  927.52   274.2  939.01   285.9  946.21
#Mann= 3 , 0 , 0
       0      .1       0    69.6    .045       0    97.2     .08       0
Bank Sta=69.6,97.2
XS Rating Curve= 0 ,0
Exp/Cntr=0.3,0.1

Type RM Length L Ch R = 1 ,4081.7  ,32.2,32.2,32.2
XS GIS Cut Line= 2
     1768061.245      359829.385     1767819.275      359948.743
#Sta/Elev= 30
       0  912.07    11.9  908.96    23.8  907.02    27.8  905.39    35.7   899.8
    43.6  892.59    47.6  889.39    51.6  886.92    55.6  885.29    63.5  882.81
    71.4  880.94    83.3  880.54    87.3  879.73    95.2  876.96    99.2  876.28
   103.2   876.2   111.1   877.5   115.1  879.09     119   880.2   146.8  880.03
   154.7  881.35   178.6  882.46   194.4  882.62   202.4  883.93   206.3  885.58
   210.3  888.08   222.2   897.4     242  911.09   261.9  921.72   269.8  925.55
#Mann= 3 , 0 , 0
       0      .1       0    87.3    .045       0   115.1     .08       0
Bank Sta=87.3,115.1
XS Rating Curve= 0 ,0
Exp/Cntr=0.3,0.1

Type RM Length L Ch R = 1 ,4049.5  ,83.8,84.9,85.9
XS GIS Cut Line= 2
     1768046.054      359801.174     1767804.084      359920.531
#Sta/Elev= 30
       0  905.69    23.8  897.39    27.8  895.45    31.7  892.47    35.7  888.28
    39.7  885.04    43.6  883.06    47.6  882.03    59.5  881.66    67.4  880.67
    79.4  880.46    83.3  879.77    87.3  878.38    91.3  877.01    95.2  876.47
   103.2  876.19   107.1   876.3   115.1  879.49   162.7  881.28   178.6  882.37
   182.5  883.18   186.5  885.01   190.4  887.53   198.4  893.78   206.3  899.21
   218.2  908.67   230.1  916.06   238.1  919.94   261.9  927.46   269.8  931.04
#Mann= 3 , 0 , 0
       0      .1       0    87.3    .045       0   115.1     .08       0
Bank Sta=87.3,115.1
XS Rating Curve= 0 ,0
Exp/Cntr=0.3,0.1

Type RM Length L Ch R = 1 ,3964.5  ,184.9,185.3,185.7
XS GIS Cut Line= 3
     1768025.438      359734.984     1767967.929       359746.92
     1767771.532      359836.981
#Sta/Elev= 30
       0  897.85    11.8   889.2    15.7   886.7    19.6  885.49    39.2  883.58
    62.7  882.05    74.4  879.53    82.3  879.05    90.2  877.14      98  875.24
   105.9  874.92   113.7  875.63   117.7   877.3   121.6  878.57   125.5  878.93
   145.2  878.95   160.9  880.39   176.6  880.58   184.4  881.65   188.4  883.82
   196.2  892.59   200.2  896.58     208  903.61   211.9  906.27   219.8  909.81
   227.7  912.02   243.4  915.11   247.3  916.43     263  923.78   274.8  930.43
#Mann= 3 , 0 , 0
       0      .1       0    90.2    .045       0   117.7     .08       0
Bank Sta=90.2,117.7
XS Rating Curve= 0 ,0
Exp/Cntr=0.3,0.1

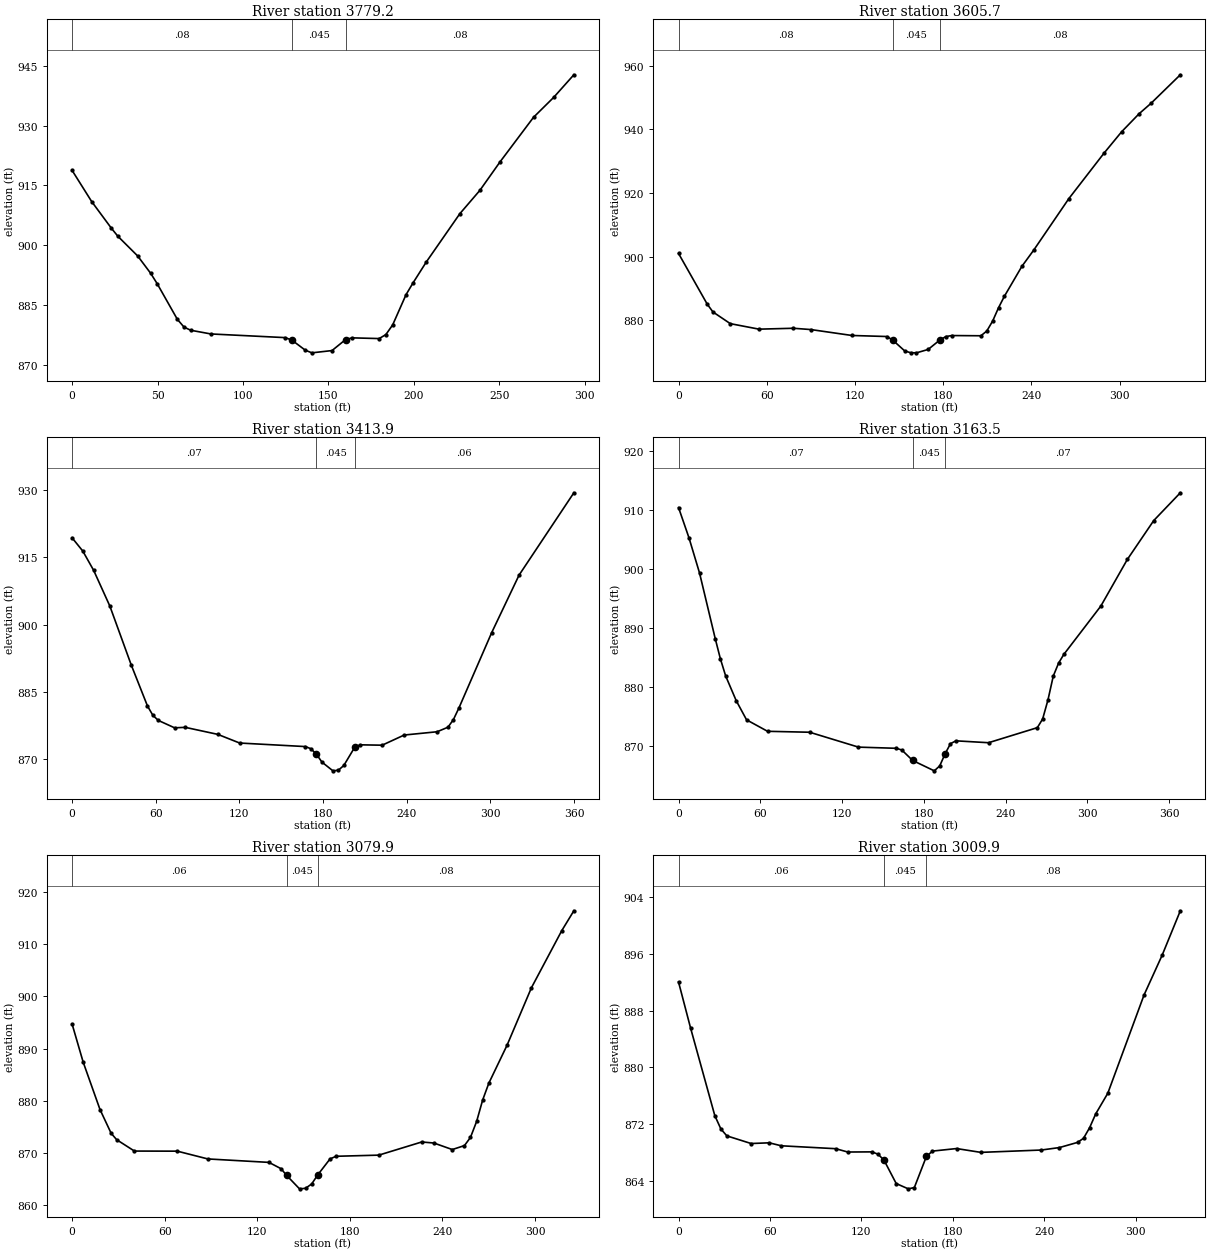
Type RM Length L Ch R = 1 ,3779.2  ,182.5,173.5,164.5
XS GIS Cut Line= 4
      1767978.78      359550.522     1767926.697      359563.543
     1767789.978      359624.307     1767705.343      359655.774
#Sta/Elev= 30
       0  918.79    11.5  910.94      23  904.27    26.8  902.25    38.4   897.3
      46  892.95    49.8  890.35    61.6  881.41    65.5  879.46    69.4  878.67
    81.2  877.74   124.6  876.82   128.5  876.23   136.4  873.68   140.3     873
   152.1  873.57     160  876.32   163.9  876.76   179.7  876.58   183.6  877.58
   187.6  880.02   195.4  887.59   199.4  890.48   207.2  895.76   226.9  907.92
   238.6  913.76   250.4  920.91     270   932.1   281.8   937.1   293.6  942.77
#Mann= 3 , 0 , 0
       0     .08       0   128.5    .045       0     160     .08       0
Bank Sta=128.5,160
XS Rating Curve= 0 ,0
Exp/Cntr=0.3,0.1

Type RM Length L Ch R = 1 ,3605.7  ,197,191.9,186.3
XS GIS Cut Line= 3
      1767901.74       359359.55     1767829.041      359397.528
     1767623.962      359555.948
#Sta/Elev= 30
       0  900.96    19.5  885.02    23.4  882.56    35.2  878.88    54.7  877.15
    78.1  877.43      90  877.02   117.9  875.16   141.8  874.83   145.8  873.64
   153.8   870.3   157.8  869.74   161.8   869.7   169.7  870.76   177.7  873.74
   181.7   874.8   185.7  875.14   205.6  875.07   209.6  876.56   213.6  879.71
   217.6   883.9   221.6  887.52   233.5  896.93   241.5     902   265.4  918.21
   289.3   932.5   301.3  939.24   313.2  944.92   321.2  948.15   341.2  957.16
#Mann= 3 , 0 , 0
       0     .08       0   145.8    .045       0   177.7     .08       0
Bank Sta=145.8,177.7
XS Rating Curve= 0 ,0
Exp/Cntr=0.3,0.1

Type RM Length L Ch R = 1 ,3413.9  ,254.7,250.4,245.9
XS GIS Cut Line= 4
     1767794.318      359185.939     1767706.428      359234.767
     1767596.836      359347.614     1767555.603       359440.93
#Sta/Elev= 30
       0  919.32     7.7  916.36    15.5  912.06    27.1  904.12    42.5  890.96
    54.1  881.86      58  879.78    61.9  878.66    73.5  877.02    81.2  877.12
   104.5  875.56   120.2  873.63   167.4  872.84   171.3  872.36   175.3  871.12
   179.2  869.39   187.1  867.44     191  867.58   194.9  868.63   202.8  872.73
   206.7  873.23   222.4  873.15   238.2  875.41   261.8  876.14   269.6  877.15
   273.5  878.84   277.5  881.46     301  898.23   320.6  911.01   359.9  929.34
#Mann= 3 , 0 , 0
       0     .07       0   175.3    .045       0   202.8     .06       0
Bank Sta=175.3,202.8
XS Rating Curve= 0 ,0
Exp/Cntr=0.3,0.1

Type RM Length L Ch R = 1 ,3163.5  ,83.2,83.6,83.9
XS GIS Cut Line= 4
     1767544.752      358989.542      1767503.52      359072.007
     1767397.183      359210.896      1767351.61      359300.957
#Sta/Elev= 30
       0  910.47     7.7   905.3    15.4  899.35    26.9  888.21    30.7  884.76
    34.6  881.83    42.3  877.65    49.9  874.39    65.3  872.44    96.2  872.28
     132  869.75   159.8  869.55   163.8  869.26   171.7  867.49   187.6  865.72
   191.6  866.56   195.6  868.64   199.5  870.34   203.5  870.82   227.4   870.5
   263.2  873.06   267.1  874.53     271  877.77   274.9  881.83   278.8  884.03
   282.6   885.5   309.8  893.73   329.2  901.64   348.6  908.26   368.1  912.98
#Mann= 3 , 0 , 0
       0     .07       0   171.7    .045       0   195.6     .07       0
Bank Sta=171.7,195.6
XS Rating Curve= 0 ,0
Exp/Cntr=0.3,0.1

Type RM Length L Ch R = 1 ,3079.9  ,68,70,72
XS GIS Cut Line= 4
     1767467.712       358972.18     1767453.607      359001.477
     1767314.718      359179.429     1767286.506      359240.193
#Sta/Elev= 30
       0  894.72     7.2   887.4    18.1  878.32    25.3  873.78    28.9  872.54
    40.4  870.36    68.2  870.34      88  868.85   127.6  868.19   135.5  866.97
     139  865.71   147.4  863.12   151.3  863.22   155.3  864.06   159.2  865.79
   167.2  868.86   171.1  869.36   198.8  869.58   226.6   872.1   234.5   871.9
   246.4  870.65   254.3  871.41   258.2  872.98   262.2  876.05   266.1  880.15
   270.1  883.37   281.9  890.64   297.7  901.66   317.4  912.62   325.2  916.41
#Mann= 3 , 0 , 0
       0     .06       0     139    .045       0   159.2     .08       0
Bank Sta=139,159.2
XS Rating Curve= 0 ,0
Exp/Cntr=0.3,0.1

Type RM Length L Ch R = 1 ,3009.9  ,36.1,36.1,36.1
XS GIS Cut Line= 2
      1767426.48      358935.288     1767210.551      359183.769
#Sta/Elev= 30
       0  892.06     7.9  885.56    23.8  873.19    27.8   871.3    31.7  870.33
    47.6  869.25    59.5  869.35    67.4  868.93   103.1  868.52     111  868.05
   126.9  868.07   130.9  867.74   134.8   866.9   142.8   863.6   150.7  862.85
   154.7  863.03   162.6  867.42   166.6  868.18   182.4  868.54   198.3     868
     238  868.33   249.9  868.68   261.8  869.41   265.7  869.99   269.7  871.49
   273.7  873.44   281.6  876.34   305.4  890.23   317.3  895.86   329.2  902.12
#Mann= 3 , 0 , 0
       0     .06       0   134.8    .045       0   162.6     .08       0
Bank Sta=134.8,162.6
XS Rating Curve= 0 ,0
Exp/Cntr=0.3,0.1