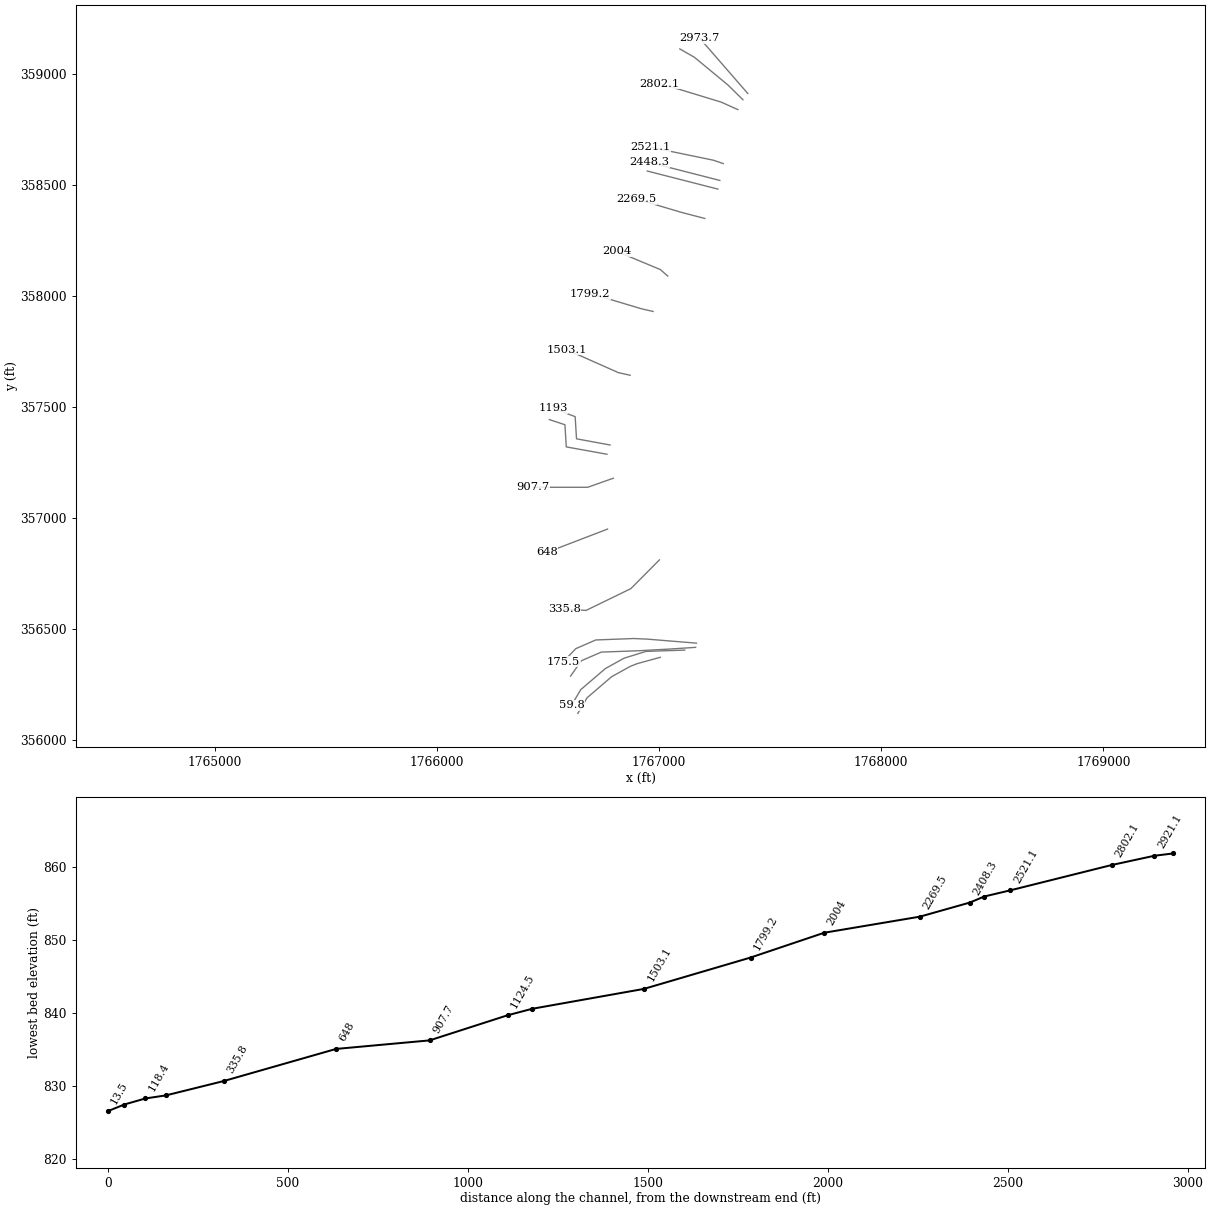
HEC-RAS study WHITESBR.prj: WHITESBR

--- WHITESBR.g01 (geometry) --- (continued)

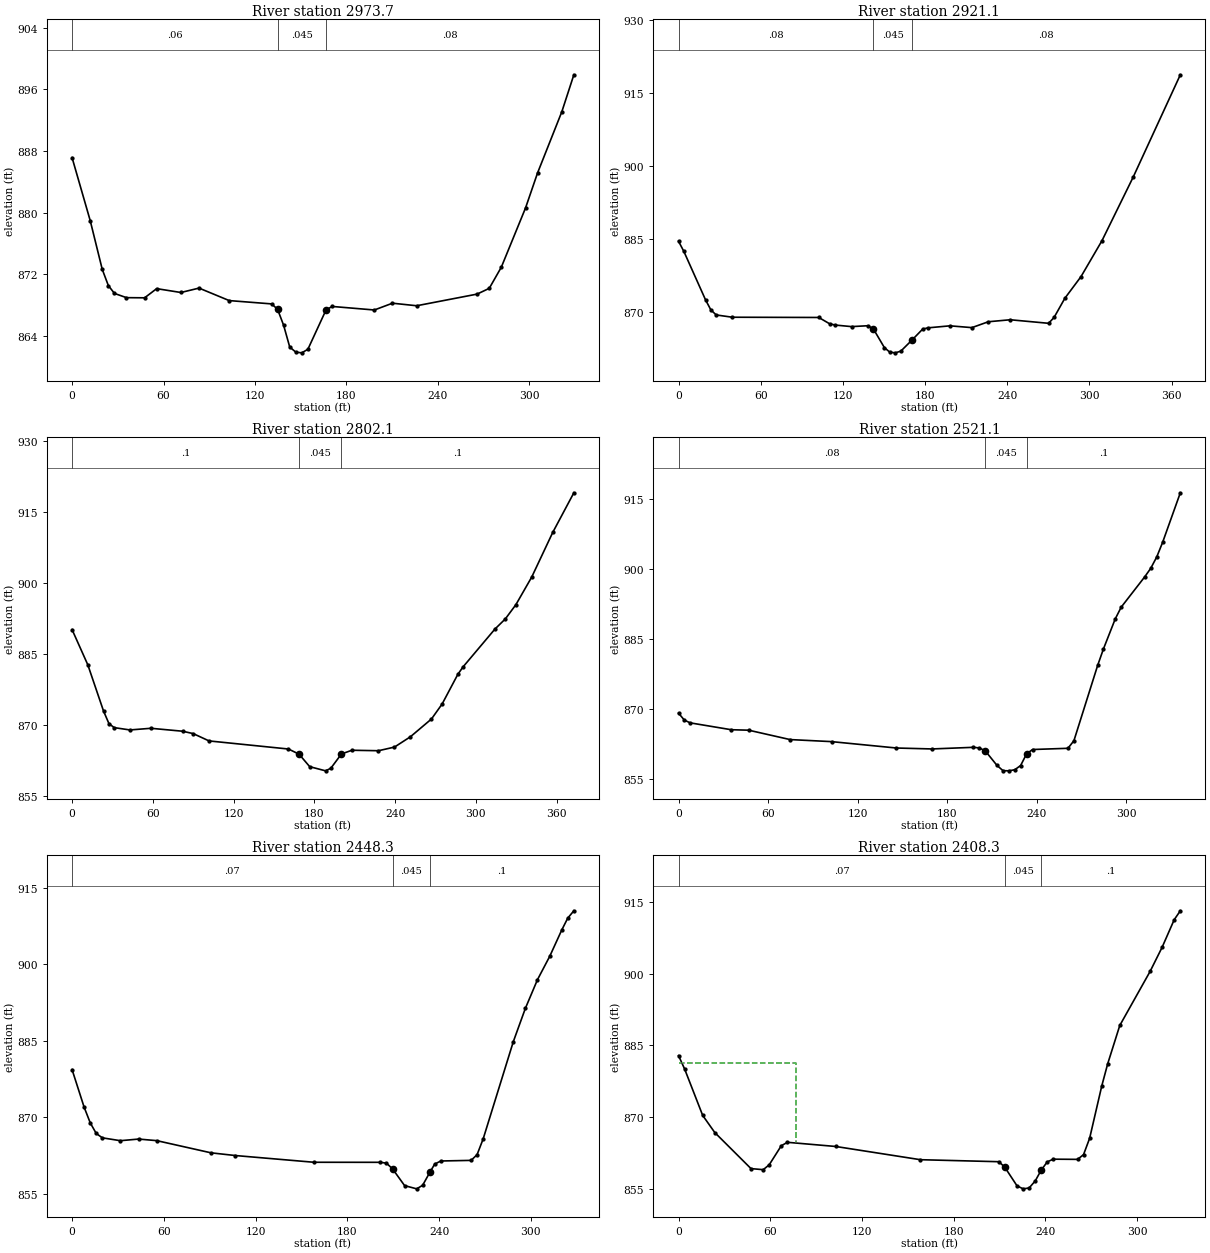
Type RM Length L Ch R = 1 ,2973.7  ,46.4,52.7,58.8
XS GIS Cut Line= 2
     1767399.353      358911.417     1767183.424      359159.897
#Sta/Elev= 30
       0  887.15    11.9  878.98    19.8  872.65    23.8  870.55    27.8  869.53
    35.7  868.98    47.6  868.96    55.5  870.15    71.4  869.65    83.3  870.22
   103.1   868.6   130.9  868.17   134.8  867.48   138.8  865.39   142.8  862.57
   146.8  861.91   150.7  861.82   154.7  862.28   166.6  867.38   170.6  867.84
   198.3  867.38   210.2  868.26   226.1  867.93   265.7  869.44   273.7  870.19
   281.6  872.93   297.5  880.62   305.4  885.17   321.3   893.1   329.2   897.9
#Mann= 3 , 0 , 0
       0     .06       0   134.8    .045       0   166.6     .08       0
Bank Sta=134.8,166.6
XS Rating Curve= 0 ,0
Exp/Cntr=0.3,0.1

Type RM Length L Ch R = 1 ,2921.1  ,103.1,118.9,134.1
XS GIS Cut Line= 4
     1767377.652      358883.205     1767310.377      358949.394
     1767159.553      359074.177     1767093.364      359112.154
#Sta/Elev= 30
       0  884.47     3.9  882.37    19.7  872.42    23.6  870.34    27.5   869.3
    39.3  868.83   102.4  868.78   110.4  867.47   114.4  867.22   126.3   866.9
   138.3  867.08   142.3  866.41   150.3  862.58   154.3  861.63   158.3   861.5
   162.3  861.85   170.3  864.08   178.3   866.4   182.3  866.65   198.2  867.06
   214.2  866.69   226.2   867.9   242.2  868.31   270.2  867.58   274.2  868.78
   282.1  872.74   293.9   877.2   309.2  884.59   332.1  897.75   366.4  918.74
#Mann= 3 , 0 , 0
       0     .08       0   142.3    .045       0   170.3     .08       0
Bank Sta=142.3,170.3
XS Rating Curve= 0 ,0
Exp/Cntr=0.3,0.1

Type RM Length L Ch R = 1 ,2802.1  ,278.4,281.1,284
XS GIS Cut Line= 4
     1767354.865      358838.717     1767279.995      358872.354
     1767095.534      358928.778     1767001.133      358954.819
#Sta/Elev= 30
       0  890.07    11.7  882.63    23.4  872.85    27.4  870.21    31.3  869.36
      43  868.87    58.6  869.22    82.1   868.6      90   868.1   101.8  866.55
   160.8  864.84   168.7  863.75   176.6  861.11   188.4  860.23   192.3  860.78
   200.2   863.8     208  864.58   227.7  864.48   239.6  865.25   251.4  867.42
   267.1  871.19     275  874.35   286.7  880.63   290.6  882.21   314.2  890.17
     322  892.34   329.8  895.33   341.6  901.18   357.2   910.6   372.9  918.98
#Mann= 3 , 0 , 0
       0      .1       0   168.7    .045       0   200.2      .1       0
Bank Sta=168.7,200.2
XS Rating Curve= 0 ,0
Exp/Cntr=0.3,0.1

Type RM Length L Ch R = 1 ,2521.1  ,74.6,72.8,71.1
XS GIS Cut Line= 3
     1767288.676      358595.661     1767244.188      358610.852
     1766960.985      358669.446
#Sta/Elev= 30
       0  869.13     3.9  867.64     7.8  867.05    35.3  865.58      47  865.48
    74.7  863.47   102.5  863.03     146  861.66   169.8  861.46   197.6  861.81
   201.5  861.68   205.5  861.05   213.4  857.92   217.4  856.81   221.3  856.77
   225.3  857.01   229.2  857.91   233.2  860.41   237.2  861.34   260.9   861.6
   264.9  863.22   280.8  879.35   284.7   882.9   292.6  889.33   296.6  891.85
   312.4  898.36   316.4  900.18   320.4   902.6   324.3   905.7   336.2  916.35
#Mann= 3 , 0 , 0
       0     .08       0   205.5    .045       0   233.2      .1       0
Bank Sta=205.5,233.2
XS Rating Curve= 0 ,0
Exp/Cntr=0.3,0.1

Type RM Length L Ch R = 1 ,2448.3  ,40,40,40
XS GIS Cut Line= 2
     1767273.485      358519.707      1766955.56      358601.087
#Sta/Elev= 30
       0   879.3     7.9  871.92    11.9  868.85    15.8  866.78    19.8  865.92
    31.6  865.36    43.5  865.68    55.4  865.37    90.9  862.98   106.8  862.45
   158.2  861.13   201.6  861.12   205.6  860.96   209.6  859.84   217.5  856.55
   225.4  855.92   229.3  856.62   234.2  859.26   237.2  860.78   241.2  861.38
     261   861.5   264.9  862.62   268.9  865.73   288.6  884.78   296.5  891.32
   304.4  896.93   312.4   901.5   320.3  906.68   324.2     909   328.2  910.44
#Mann= 3 , 0 , 0
       0     .07       0   209.6    .045       0   234.2      .1       0
Bank Sta=209.6,234.2
XS Rating Curve= 0 ,0
Exp/Cntr=0.3,0.1

Type RM Length L Ch R = 1 ,2408.3  ,140.2,138.8,137.4
XS GIS Cut Line= 2
     1767264.804      358480.644     1766946.879      358562.024
#Sta/Elev= 30
       0  882.89       4  880.08    15.8  870.41    23.7  866.84    47.4  859.31
    55.4  859.09    59.3   860.1    67.2  864.08    71.2   864.8   102.8  863.93
   158.2  861.17   209.6  860.75   213.5  859.55   221.4  855.71   225.4  855.09
   229.3  855.27   233.3  856.74   237.2  858.99   241.2  860.73   245.1  861.28
     261  861.24   264.9  862.23   268.9  865.66   276.8  876.54   280.7  881.19
   288.6  889.18   308.4  900.44   316.3   905.5   324.2  911.25   328.2  913.11
#Mann= 3 , 0 , 0
       0     .07       0   213.5    .045       0   237.2      .1       0
#XS Ineff= 2 , 0
           76.88  881.43
Permanent Ineff=
       F       F
Bank Sta=213.5,237.2
XS Rating Curve= 0 ,0
Exp/Cntr=0.3,0.1

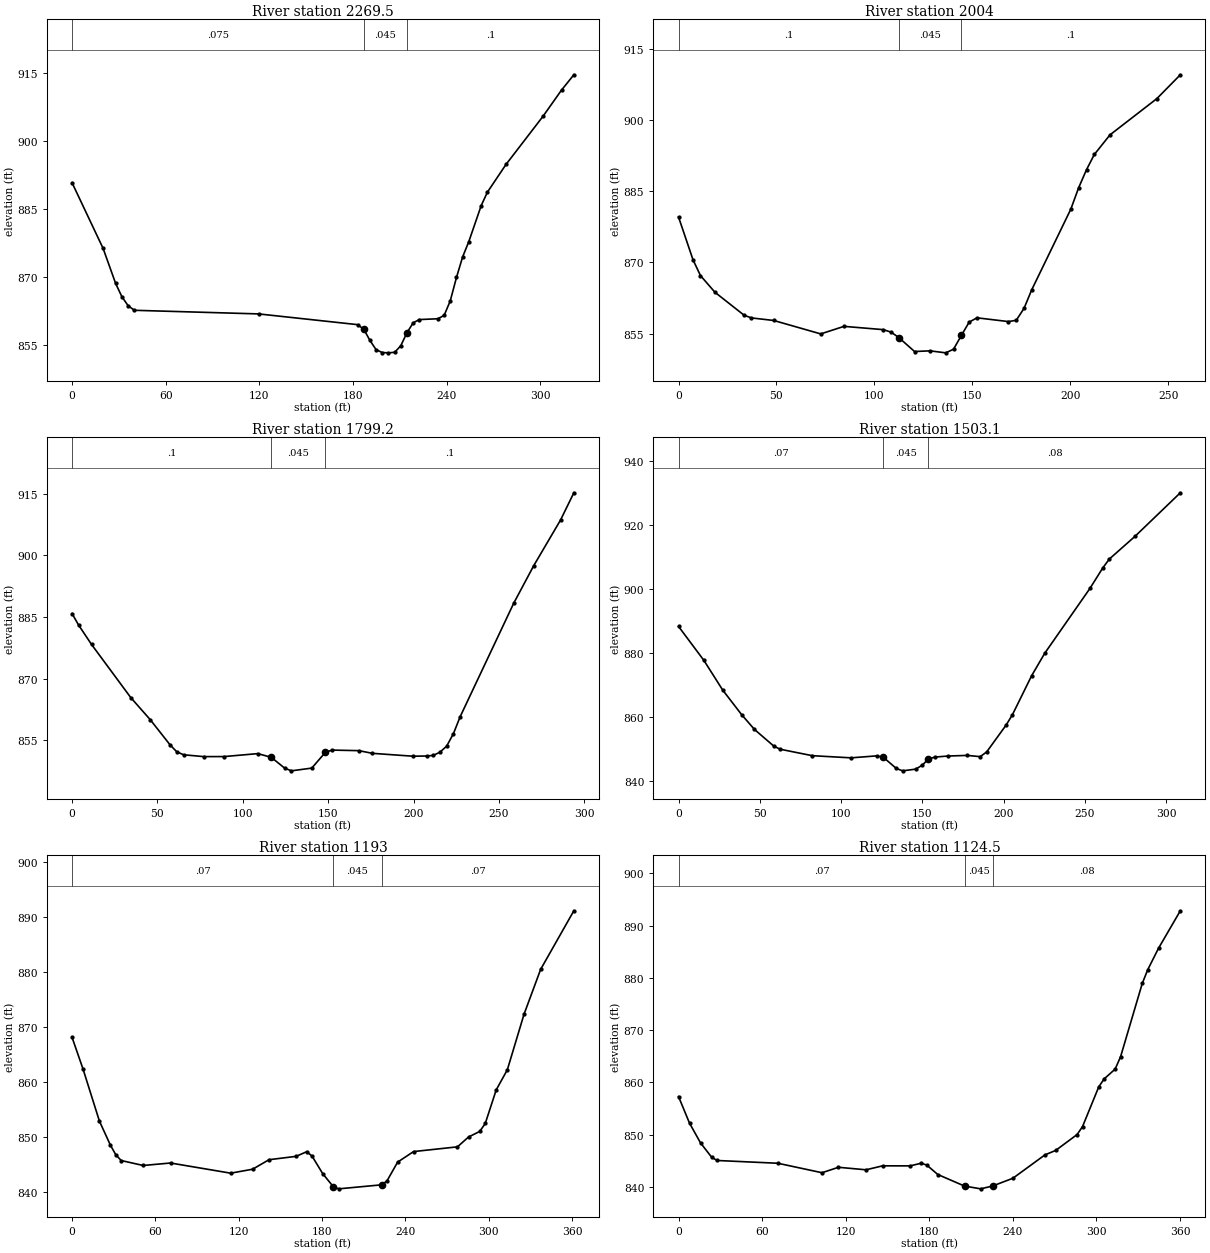
Type RM Length L Ch R = 1 ,2269.5  ,269.5,265.5,261.5
XS GIS Cut Line= 3
     1767206.211      358348.266     1767102.044      358375.392
     1766896.966      358436.156
#Sta/Elev= 30
       0  890.73    19.9  876.22    27.9   868.5    31.9  865.57    35.9  863.58
    39.9  862.56   119.5  861.76   182.9  859.39   186.9  858.38   190.8  855.92
   194.8  853.86   198.7  853.23   202.7  853.16   206.7  853.28   210.6  854.72
   214.6  857.63   218.6  859.81   222.5  860.51   234.4  860.69   238.4  861.44
   242.3  864.63   246.3  869.82   250.2  874.32   254.2  877.74   262.1  885.66
   266.1  888.65     278  894.77   301.7   905.4   313.6  911.21   321.5  914.59
#Mann= 3 , 0 , 0
       0    .075       0   186.9    .045       0   214.6      .1       0
Bank Sta=186.9,214.6
XS Rating Curve= 0 ,0
Exp/Cntr=0.3,0.1

Type RM Length L Ch R = 1 ,2004    ,200.8,204.8,208.6
XS GIS Cut Line= 3
      1767039.11      358088.934     1767005.473      358118.231
      1766810.16      358199.611
#Sta/Elev= 30
       0  879.58     7.4  870.56    11.2  867.24    18.6  863.72    33.5  858.88
    37.2  858.32    48.6  857.78    72.6  854.95    84.5  856.54   104.5  855.85
   108.5  855.33   112.5  854.17   120.5  851.24   128.4  851.38   136.4  850.96
   140.4  851.72   144.4  854.62   148.4  857.44   152.4  858.34   168.4  857.55
   172.4  857.81   176.4  860.33   180.3  864.22   200.3  881.25   204.3  885.77
   208.3  889.56   212.3  892.77   220.3   896.9   244.2  904.53   256.2  909.56
#Mann= 3 , 0 , 0
       0      .1       0   112.5    .045       0   144.4      .1       0
Bank Sta=112.5,144.4
XS Rating Curve= 0 ,0
Exp/Cntr=0.3,0.1

Type RM Length L Ch R = 1 ,1799.2  ,301,296.1,291.5
XS GIS Cut Line= 4
     1766972.921      357929.429     1766920.837      357941.364
     1766750.482      357992.363     1766689.718      358007.554
#Sta/Elev= 30
       0  885.82     3.8  883.04    11.4  878.31    34.4  865.37    45.8     860
    57.4  853.88    61.3   852.2    65.3  851.47    77.1  851.02      89  851.03
   108.8  851.75   116.7  850.84   124.6  848.19   128.5  847.56   140.4  848.23
   148.3  852.03   152.2  852.61     168  852.47   175.9  851.82   199.6  851.12
   207.6  851.17   211.5  851.31   215.4  852.08   219.4  853.56   223.4  856.64
   227.3  860.73   258.7  888.36   270.4  897.48   286.1  908.58   293.9  915.21
#Mann= 3 , 0 , 0
       0      .1       0   116.7    .045       0   148.3      .1       0
Bank Sta=116.7,148.3
XS Rating Curve= 0 ,0
Exp/Cntr=0.3,0.1

Type RM Length L Ch R = 1 ,1503.1  ,353.6,310.1,261.7
XS GIS Cut Line= 3
     1766869.839      357641.885     1766816.671      357653.821
     1766584.466      357756.903
#Sta/Elev= 30
       0  888.37    15.6  877.76    27.2  868.47    38.9  860.76    46.7   856.2
    58.5  851.03    62.4  850.03    82.3     848   106.1  847.33     122  847.95
     126  847.49   133.9  844.02   137.8  843.27   145.8   843.8   149.8     845
   153.7  846.95   157.7  847.57   165.6  847.89   177.6  848.09   185.5   847.7
   189.5  849.17   201.4  857.52   205.3  860.75   217.2  873.02   225.2  879.98
     253  900.23   260.9  906.63   264.9  909.39   280.8  916.54   308.6  930.11
#Mann= 3 , 0 , 0
       0     .07       0     126    .045       0   153.7     .08       0
Bank Sta=126,153.7
XS Rating Curve= 0 ,0
Exp/Cntr=0.3,0.1

Type RM Length L Ch R = 1 ,1193    ,47.7,68.5,63.4
XS GIS Cut Line= 4
      1766779.31      357327.775     1766628.268      357355.553
     1766622.192       357455.38     1766521.497      357493.574
#Sta/Elev= 30
       0   868.1     7.9  862.34    19.7  852.87    27.6   848.5    31.5  846.74
    35.4   845.7    51.2   844.8    70.9  845.25   114.2   843.4     130  844.12
   141.8  845.85   161.3  846.46     169  847.31   172.8   846.5   180.5   843.3
   188.2  840.91     192  840.55   222.8  841.28   226.7  841.97   234.4  845.41
   245.9  847.33   277.5  848.19   285.5  849.99   293.5  850.99   297.5  852.44
   305.4  858.56   313.4  862.21   325.4   872.3   337.4  880.49   361.3  891.14
#Mann= 3 , 0 , 0
       0     .07       0   188.2    .045       0   222.8     .07       0
Bank Sta=188.2,222.8
XS Rating Curve= 0 ,0
Exp/Cntr=0.3,0.1

Type RM Length L Ch R = 1 ,1124.5  ,178.3,216.7,284.6
XS GIS Cut Line= 4
     1766765.421      357286.109     1766582.261      357319.095
     1766576.185      357418.921     1766505.872      357442.359
#Sta/Elev= 30
       0   857.3     7.9  852.21    15.8  848.44    23.8  845.69    27.7  845.08
    71.3  844.55     103  842.74   114.8  843.78   134.6   843.3   146.5  844.06
   166.3  844.05   174.2  844.56   178.2   844.2   186.1   842.4   205.3  840.19
   216.9  839.66   225.4   840.2     240  841.68     263  846.15   270.7     847
   286.1  850.04     290  851.56   301.7  859.19   305.6   860.7   313.4  862.55
   317.3  864.91   332.9  878.95   336.8  881.55   344.6  885.68   360.2  892.82
#Mann= 3 , 0 , 0
       0     .07       0   205.3    .045       0   225.4     .08       0
Bank Sta=205.3,225.4
XS Rating Curve= 0 ,0
Exp/Cntr=0.3,0.1

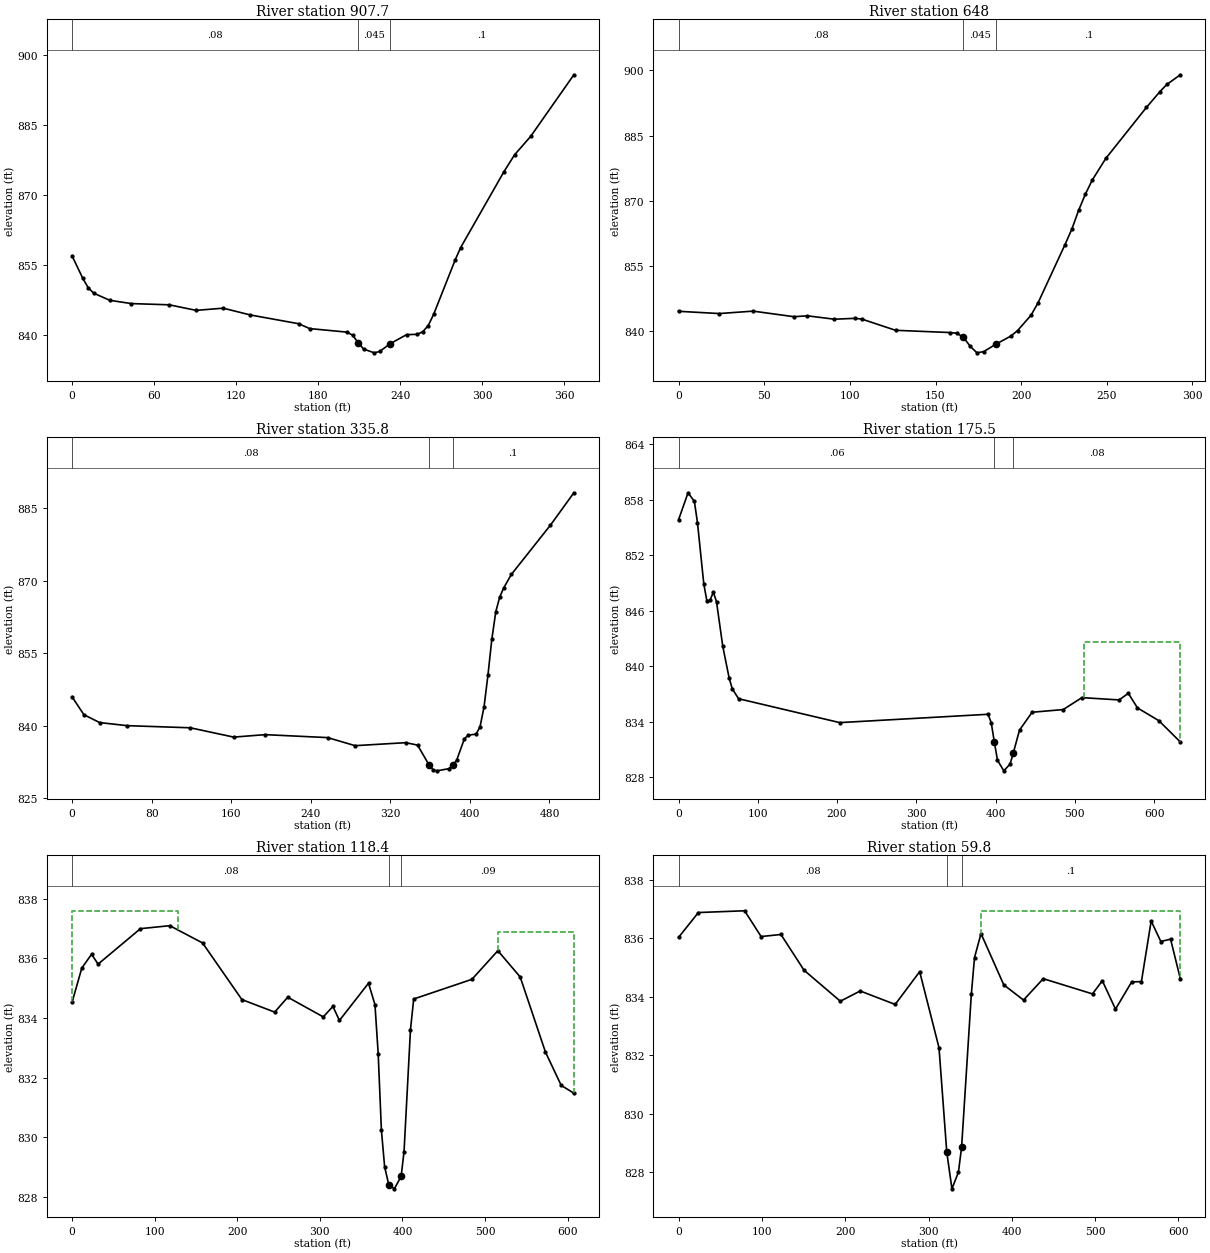
Type RM Length L Ch R = 1 ,907.7   ,245.2,259.8,273.5
XS GIS Cut Line= 3
     1766793.971      357178.018      1766678.52       357137.22
     1766433.728       357137.22
#Sta/Elev= 30
       0  856.94     7.9  852.12    11.8  850.16    15.8  848.98    27.6  847.45
    43.4  846.75    71.1  846.49    90.8   845.3   110.6  845.77   130.4  844.32
   165.9  842.44   173.8  841.41   201.4  840.64   205.4  839.96   209.3  838.42
   213.3  837.02   221.2  836.22   225.1  836.52     233  838.21   244.8  840.11
   252.7  840.18   256.7  840.76   260.6  842.04   264.6  844.45   280.4  856.12
   284.3   858.7   315.9  874.88   323.8  878.56   335.6   882.5   367.2  895.67
#Mann= 3 , 0 , 0
       0     .08       0   209.3    .045       0     233      .1       0
Bank Sta=209.3,233
XS Rating Curve= 0 ,0
Exp/Cntr=0.3,0.1

Type RM Length L Ch R = 1 ,648     ,308.1,312.2,315
XS GIS Cut Line= 2
     1766767.929      356948.851     1766494.492      356843.817
#Sta/Elev= 30
       0   844.6    23.8  844.08    43.5  844.64    67.3  843.36    75.2  843.56
      91  842.78   102.9  842.98   106.9  842.82   126.7  840.23   158.3  839.72
   162.3  839.56   166.2  838.69   170.2  836.57   174.2  835.05   178.1  835.33
   185.5  837.09     194  838.91   197.9  840.17   205.8  843.72   209.8   846.5
   225.6  859.94   229.6  863.51   233.5  867.78   237.5  871.55   241.5  874.77
   249.4  879.74   273.1  891.46     281   895.1     285  896.74   292.9  898.97
#Mann= 3 , 0 , 0
       0     .08       0   166.2    .045       0   185.5      .1       0
Bank Sta=166.2,185.5
XS Rating Curve= 0 ,0
Exp/Cntr=0.3,0.1

Type RM Length L Ch R = 1 ,335.8   ,175.8,160.3,145
XS GIS Cut Line= 4
     1767001.436      356809.963     1766872.964      356680.622
     1766671.575      356582.532     1766573.485       356587.74
#Sta/Elev= 30
       0  845.96    11.9  842.27    27.7  840.64    55.5     840   118.9  839.56
   162.5  837.63   194.1  838.14     257  837.53   284.5  835.86   335.6  836.48
   347.4  835.97   359.2  831.76   363.1  830.83     367  830.65   378.8   831.1
   382.7  831.81   386.7  832.86   394.5  837.32   398.4  838.02   406.3  838.27
   410.2   839.8   414.2   843.9   418.1  850.42     422  857.84     426  863.57
   429.9  866.58   433.8  868.45   441.7  871.31     481  881.51   504.5   888.2
#Mann= 3 , 0 , 0
       0     .08       0   359.2    .045       0   382.7      .1       0
Bank Sta=359.2,382.7
XS Rating Curve= 0 ,0
Exp/Cntr=0.3,0.1

Type RM Length L Ch R = 1 ,175.5   ,57.3,57,58.5
XS GIS Cut Line= 6
     1767168.103      356434.963     1766945.447      356453.192
     1766885.551      356455.796     1766714.978      356449.285
     1766625.134      356410.223     1766569.145      356351.629
#Sta/Elev= 30
       0  855.81      12  858.73      20   857.8    23.9   855.5    31.9  848.86
    35.9  846.99    39.9  847.15    43.9     848    47.9  846.96    55.8  842.15
    63.8  838.74    67.8  837.55    75.8  836.48   203.4   833.9   390.5   834.8
   394.5   833.9   398.5  831.77   402.4  829.84   410.4  828.69   418.3  829.42
   422.3   830.6   430.2  833.09   446.1  835.02   485.4  835.31   508.9   836.6
   555.9  836.35   567.5  837.07     579  835.49     606  834.11   633.1  831.81
#Mann= 3 , 0 , 0
       0     .06       0   398.5    .045       0   422.3     .08       0
#XS Ineff= 2 , 0
                          512.13          842.59
Permanent Ineff=
       F       F
Bank Sta=398.5,422.3
XS Rating Curve= 0 ,0
Exp/Cntr=0.3,0.1

Type RM Length L Ch R = 1 ,118.4   ,40.8,58.7,74.9
XS GIS Cut Line= 6
     1767164.509      356416.048     1767050.433      356408.488
     1766907.783      356400.777     1766739.718      356394.598
     1766649.874      356355.535     1766601.697      356286.525
#Sta/Elev= 30
       0  834.53    11.8  835.68    23.6  836.14    31.5  835.81    82.8     837
   118.3   837.1     158  836.52   205.6  834.62   245.3   834.2   261.1   834.7
   304.1  834.04   315.8  834.39   323.7  833.92   358.9  835.17   366.7  834.45
   370.6  832.81   374.5  830.24   378.4  829.01   383.4  828.41   390.2  828.27
   398.4  828.69   401.9  829.52   409.7  833.61   413.6  834.64   484.1   835.3
   515.5  836.26   542.5  835.38   573.1  832.86   592.2  831.74   607.5  831.48
#Mann= 3 , 0 , 0
       0     .08       0   383.4    .045       0   398.4     .09       0
#XS Ineff= 2 , 0
          128.34   837.6  515.23          836.89
Permanent Ineff=
       F       F
Bank Sta=383.4,398.4
XS Rating Curve= 0 ,0
Exp/Cntr=0.3,0.1

Type RM Length L Ch R = 1 ,59.8    ,46.2,46.2,46.2
XS GIS Cut Line= 6
     1767115.551      356403.548     1766941.204      356397.858
     1766842.582      356367.254     1766757.947      356320.379
      1766647.27      356225.327     1766605.603      356155.015
#Sta/Elev= 30
       0  836.03    23.8  836.88    79.3  836.94    99.1  836.06   122.9  836.13
   150.6  834.91   194.2  833.85     218   834.2     260  833.74   289.4  834.86
   312.6  832.26   321.9   828.7   328.1  827.44   335.9  828.01   339.7  828.86
   351.4  834.09   355.2  835.34     363  836.16   390.3  834.41     414  833.89
   437.7  834.62   496.8   834.1   508.6  834.55   524.4  833.58   543.8  834.51
   555.5  834.52   567.2  836.59   578.8  835.89   590.5  835.97   602.2  834.62
#Mann= 3 , 0 , 0
       0     .08       0   321.9    .045       0   339.7      .1       0
#XS Ineff= 2 , 0
                          362.71          836.93
Permanent Ineff=
       F       F
Bank Sta=321.9,339.7
XS Rating Curve= 0 ,0
Exp/Cntr=0.3,0.1

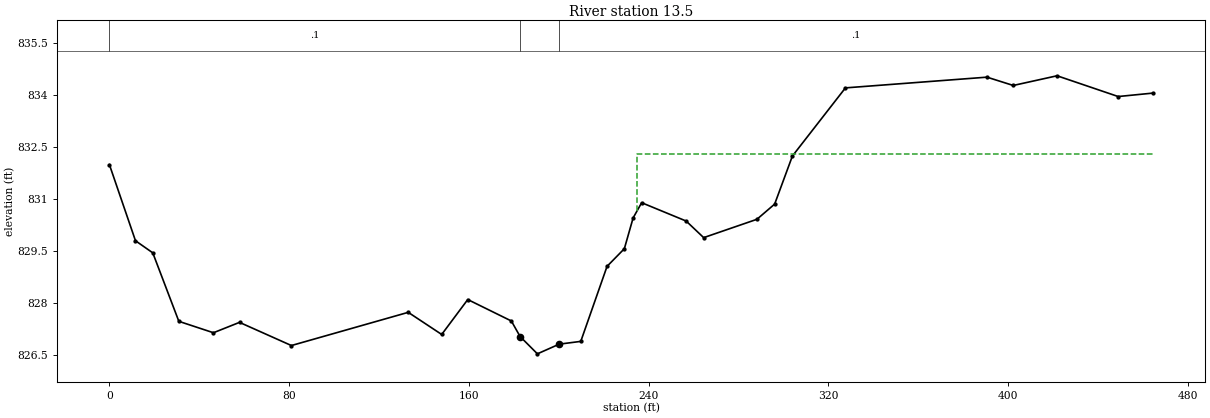
Type RM Length L Ch R = 1 ,13.5    ,8.3,13.5,18.8
XS GIS Cut Line= 6
     1767005.343       356371.16     1766901.176      356342.515
     1766871.228      356330.796     1766786.593      356283.921
     1766675.916      356188.869     1766634.249      356118.556
#Sta/Elev= 30
       0  831.99    11.6  829.79    19.3  829.44    30.9  827.46    46.3  827.13
    57.9  827.43      81  826.76     133  827.72   147.9  827.08   159.5  828.09
   178.9  827.47   182.8  827.02   190.5  826.52   200.2   826.8   209.8  826.88
   221.5  829.05   229.2  829.56   233.1  830.45   236.9  830.89   256.7  830.36
   264.5  829.88   288.2  830.41   296.1  830.85     304  832.24   327.6  834.21
   390.6  834.52   402.3  834.28   421.8  834.56     449  833.96   464.6  834.06
#Mann= 3 , 0 , 0
       0      .1       0   182.8    .045       0   200.2      .1       0
#XS Ineff= 2 , 0
                          234.72          832.31
Permanent Ineff=
       F       F
Bank Sta=182.8,200.2
XS Rating Curve= 0 ,0
Exp/Cntr=0.3,0.1

Chan Stop Cuts=-1
Use User Specified Reach Order=0
Composite Channel Slope=5